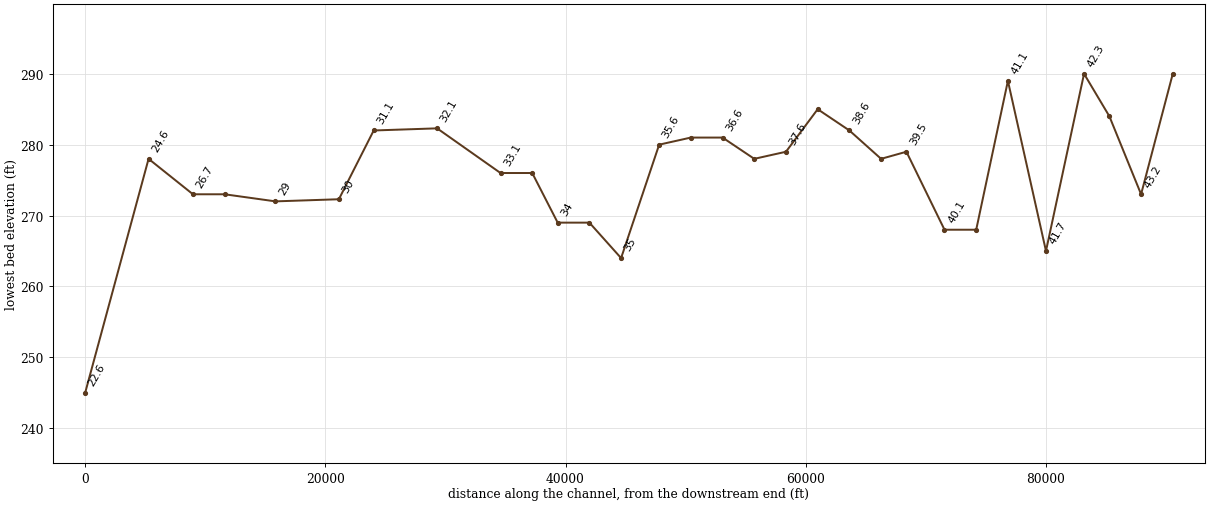
--- MissOhioRiv.prj (project) ---

Proj Title=Mississippi - Ohio River System
Current Plan=p01
Default Exp/Contr=0.3,0.1
English Units
Geom File=g01
Unsteady File=u01
Plan File=p01
Y Axis Title=Elevation
X Axis Title(PF)=Main Channel Distance
X Axis Title(XS)=Station
BEGIN DESCRIPTION:
END DESCRIPTION:
DSS Start Date=01OCT1984
DSS Start Time=2400
DSS End Date=30SEP1985
DSS End Time=2400
DSS File=dss
DSS File=DSS
DSS Export Rating Curves= 0
DSS Export Rating Curve Sorted= 0
DSS Export Volume Flow Curves= 0
DXF Filename=DSSPlot.dxf
DXF OffsetX= 0
DXF OffsetY= 0
DXF ScaleX= 1
DXF ScaleY= 10

--- MissOhioRiv.p01 (plan) ---

Plan Title=1985 Flood Calibration
Program Version=6.20
Short Identifier=Flood Cal
Simulation Date=01OCT1984,2400,30SEP1985,1200
Geom File=g01
Flow File=u01
Subcritical Flow
K Sum by GR= 0
Std Step Tol= 0.01
Critical Tol= 0.01
Num of Std Step Trials= 20
Max Error Tol= 0.3
Flow Tol Ratio= 0.001
Split Flow NTrial= 30
Split Flow Tol= 0.02
Split Flow Ratio= 0.02
Log Output Level= 0
Friction Slope Method= 1
Unsteady Friction Slope Method= 2
Unsteady Bridges Friction Slope Method= 1
Parabolic Critical Depth
Global Vel Dist= 0 , 0 , 0
Global Log Level= 0
CheckData=True
Encroach Param=-1 ,0,0, 0
Computation Interval=1HOUR
Output Interval=1DAY
Instantaneous Interval=1WEEK
Mapping Interval=6HOUR
Computation Time Step Use Courant=        0
Computation Time Step Use Time Series=    0
Computation Time Step Count To Double=0
Computation Time Step Max Doubling=0
Computation Time Step Max Halving=0
Computation Time Step Residence Courant=0
Run HTab=-1
Run UNet=-1
Run Sediment= 0
Run PostProcess=-1
Run WQNet= 0
Run RASMapper= 0
UNET Theta= 1
UNET Theta Warmup= 1
UNET ZTol= 0.02
UNET ZSATol= 0.1
UNET MxIter= 20
UNET Max Iter WO Improvement= 0
UNET MaxInSteps= 20
UNET DtIC= 0
UNET DtMin= 0
UNET MaxCRTS= 20
UNET WFStab= 2
UNET SFStab= 1
UNET WFX= 1
UNET SFX= 1
UNET Gravity=32.174
UNET 1D Methodology=Finite Difference
UNET DSS MLevel= 4
UNET Pardiso=0
UNET DZMax Abort= 100
UNET Use Existing IB Tables=-1
UNET Froude Reduction=False
UNET Froude Limit= 0.8
UNET Froude Power= 4
UNET D1 Cores= 0
UNET WindReference=Eulerian
UNET WindDragFormulation=Hsu (1988)
UNET D2 Coriolis=0
UNET D2 Cores= 0
UNET D2 Theta= 1
UNET D2 Theta Warmup= 1
UNET D2 Z Tol= 0.01
UNET D2 Volume Tol= 0.01
UNET D2 Max Iterations= 20
UNET D2 Equation= 0
UNET D2 RampUpFraction=0.1
UNET D2 TimeSlices= 1
UNET D2 Turbulence Formulation=Non-Conservative (original)
UNET D2 Smagorinsky Mixing=0
UNET D2 BCVolumeCheck=0
UNET D2 Cores=0
UNET D2 SolverType=PARDISO (Direct)
UNET D2 Minimum Iterations= 2147483647
UNET D2 Maximum Iterations= 2147483647
UNET D2 Restart Number= 10
UNET D2 Relaxation Coeff=1.3
UNET D2 SOR Precondition Iterations= 10
UNET D2 ILUT Maximum Fill= 8
UNET D2 ILUT Tolerance=1E-08
UNET D1D2 MaxIter= 0
UNET D1D2 ZTol=0.01
UNET D1D2 QTol=0.1
UNET D1D2 MinQTol=1
DSS File=dss
Write IC File= 0
Write IC File at Fixed DateTime=0
Write IC File at Sim End=0
Echo Input=False
Echo Parameters=False
Echo Output=False
Write Detailed= 0
HDF Write Warmup=0
HDF Write Time Slices=0
HDF Flush=0
HDF Compression= 1
HDF Chunk Size= 1
HDF Spatial Parts= 1
HDF Use Max Rows=0
HDF Fixed Rows= 1
Stage Flow Hydrograph=Mississippi Riv ,Upper           ,43.7
Stage Flow Hydrograph=Mississippi Riv ,Upper           ,43.2
Stage Flow Hydrograph=Mississippi Riv ,Upper           ,42.7
Stage Flow Hydrograph=Mississippi Riv ,Upper           ,42.3
Stage Flow Hydrograph=Mississippi Riv ,Upper           ,41.7
Stage Flow Hydrograph=Mississippi Riv ,Upper           ,41.1
Stage Flow Hydrograph=Mississippi Riv ,Upper           ,40.6
Stage Flow Hydrograph=Mississippi Riv ,Upper           ,40.1
Stage Flow Hydrograph=Mississippi Riv ,Upper           ,39.5
Stage Flow Hydrograph=Mississippi Riv ,Upper           ,39.1
Stage Flow Hydrograph=Mississippi Riv ,Upper           ,38.6
Stage Flow Hydrograph=Mississippi Riv ,Upper           ,38.1
Stage Flow Hydrograph=Mississippi Riv ,Upper           ,37.6
Stage Flow Hydrograph=Mississippi Riv ,Upper           ,37.1
Stage Flow Hydrograph=Mississippi Riv ,Upper           ,36.6
Stage Flow Hydrograph=Mississippi Riv ,Upper           ,36.1
Stage Flow Hydrograph=Mississippi Riv ,Upper           ,35.6
Stage Flow Hydrograph=Mississippi Riv ,Upper           ,35
Stage Flow Hydrograph=Mississippi Riv ,Upper           ,34.5
Stage Flow Hydrograph=Mississippi Riv ,Upper           ,34
Stage Flow Hydrograph=Mississippi Riv ,Upper           ,33.6
Stage Flow Hydrograph=Mississippi Riv ,Upper           ,33.1
Stage Flow Hydrograph=Mississippi Riv ,Upper           ,32.1
Stage Flow Hydrograph=Mississippi Riv ,Upper           ,31.1
Stage Flow Hydrograph=Mississippi Riv ,Upper           ,30
Stage Flow Hydrograph=Mississippi Riv ,Upper           ,29
Stage Flow Hydrograph=Mississippi Riv ,Upper           ,28.2
Stage Flow Hydrograph=Mississippi Riv ,Upper           ,26.7
Stage Flow Hydrograph=Mississippi Riv ,Upper           ,24.6
Stage Flow Hydrograph=Mississippi Riv ,Upper           ,22.6
Stage Flow Hydrograph=Mississippi Riv ,Upper           ,21.2
Stage Flow Hydrograph=Mississippi Riv ,Upper           ,20.2
Stage Flow Hydrograph=Mississippi Riv ,Upper           ,19.4
Stage Flow Hydrograph=Mississippi Riv ,Upper           ,17.1
Stage Flow Hydrograph=Mississippi Riv ,Upper           ,15
Stage Flow Hydrograph=Mississippi Riv ,Upper           ,13.2
Stage Flow Hydrograph=Mississippi Riv ,Upper           ,13
Stage Flow Hydrograph=Mississippi Riv ,Upper           ,12
Stage Flow Hydrograph=Mississippi Riv ,Upper           ,11
Stage Flow Hydrograph=Mississippi Riv ,Upper           ,10
Stage Flow Hydrograph=Mississippi Riv ,Upper           ,9
Stage Flow Hydrograph=Mississippi Riv ,Upper           ,8.2
Stage Flow Hydrograph=Mississippi Riv ,Upper           ,7.6
Stage Flow Hydrograph=Mississippi Riv ,Upper           ,7.517
Stage Flow Hydrograph=Mississippi Riv ,Upper           ,7.515
Stage Flow Hydrograph=Mississippi Riv ,Upper           ,7.502
Stage Flow Hydrograph=Mississippi Riv ,Upper           ,7.5
Stage Flow Hydrograph=Mississippi Riv ,Upper           ,6.9
Stage Flow Hydrograph=Mississippi Riv ,Upper           ,6.2
Stage Flow Hydrograph=Mississippi Riv ,Upper           ,5.6
Stage Flow Hydrograph=Mississippi Riv ,Upper           ,5.1
Stage Flow Hydrograph=Mississippi Riv ,Upper           ,4.5
Stage Flow Hydrograph=Mississippi Riv ,Upper           ,3.9
Stage Flow Hydrograph=Mississippi Riv ,Upper           ,3.4
Stage Flow Hydrograph=Mississippi Riv ,Upper           ,2.7
Stage Flow Hydrograph=Mississippi Riv ,Upper           ,2
Stage Flow Hydrograph=Mississippi Riv ,Upper           ,1.4
Stage Flow Hydrograph=Mississippi Riv ,Upper           ,0
Stage Flow Hydrograph=Mississippi Riv ,Lower           ,953.03
Stage Flow Hydrograph=Mississippi Riv ,Lower           ,949
Stage Flow Hydrograph=Mississippi Riv ,Lower           ,944.75
Stage Flow Hydrograph=Mississippi Riv ,Lower           ,940.79
Stage Flow Hydrograph=Mississippi Riv ,Lower           ,936.38
Stage Flow Hydrograph=Mississippi Riv ,Lower           ,931.53
Stage Flow Hydrograph=Mississippi Riv ,Lower           ,927.5
Stage Flow Hydrograph=Mississippi Riv ,Lower           ,923.46
Stage Flow Hydrograph=Mississippi Riv ,Lower           ,922
Stage Flow Hydrograph=Ohio River      ,Main Stem       ,17.39
Stage Flow Hydrograph=Ohio River      ,Main Stem       ,17
Stage Flow Hydrograph=Ohio River      ,Main Stem       ,16
Stage Flow Hydrograph=Ohio River      ,Main Stem       ,15
Stage Flow Hydrograph=Ohio River      ,Main Stem       ,13.94
Stage Flow Hydrograph=Ohio River      ,Main Stem       ,13
Stage Flow Hydrograph=Ohio River      ,Main Stem       ,12
Stage Flow Hydrograph=Ohio River      ,Main Stem       ,11
Stage Flow Hydrograph=Ohio River      ,Main Stem       ,10
Stage Flow Hydrograph=Ohio River      ,Main Stem       ,9
Stage Flow Hydrograph=Ohio River      ,Main Stem       ,8
Stage Flow Hydrograph=Ohio River      ,Main Stem       ,7
Stage Flow Hydrograph=Ohio River      ,Main Stem       ,5.9
Stage Flow Hydrograph=Ohio River      ,Main Stem       ,5
Stage Flow Hydrograph=Ohio River      ,Main Stem       ,3.9
Stage Flow Hydrograph=Ohio River      ,Main Stem       ,3
Stage Flow Hydrograph=Ohio River      ,Main Stem       ,2
Stage Flow Hydrograph=Ohio River      ,Main Stem       ,0.9
Stage Flow Hydrograph=Ohio River      ,Main Stem       ,0
Calibration Method= 0
Calibration Iterations= 20
Calibration Max Change=0.05
Calibration Tolerance=0.2
Calibration Maximum=1.5
Calibration Minimum=0.5
Calibration Optimization Method= 1
WQ AD Non Conservative
WQ ULTIMATE=-1
WQ Max Comp Step=1HOUR
WQ Output Interval=15MIN
WQ Output Selected Increments= 0
WQ Output face flow=0
WQ Output face velocity=0
WQ Output face area=0
WQ Output face dispersion=0
WQ Output cell volume=0
WQ Output cell surface area=0
WQ Output cell continuity=0
WQ Output cumulative cell continuity=0
WQ Output face conc=0
WQ Output face dconc_dx=0
WQ Output face courant=0
WQ Output face peclet=0
WQ Output face adv mass=0
WQ Output face disp mass=0
WQ Output cell mass=0
WQ Output cell source sink temp=0
WQ Output nsm pathways=0
WQ Output nsm derived pathways=0
WQ Create Restart=0
WQ Fixed Restart=0
WQ System Summary=0
WQ Write To DSS=0
Sorting and Armoring Iterations= 10
XS Update Threshold= 0.02
Bed Roughness Predictor= 0
Hydraulics Update Threshold= 0.02
Energy Slope Method= 1
Volume Change Method= 1
Sediment Retention Method= 0
Sediment TS Multiplier= 1
Warm Up Method= 0
XS Weighting Method= 0
Number of US Weighted Cross Sections= 1
Number of DS Weighted Cross Sections= 1
Upstream XS Weight=0
Main XS Weight=1
Downstream XS Weight=0
Number of DS XS's Weighted with US Boundary= 1
Upstream Boundary Weight= 1
Weight of XSs Associated with US Boundary= 0
Number of US XS's Weighted with DS Boundary= 1
Downstream Boundary Weight= 0.5
Weight of XSs Associated with DS Boundary= 0.5
Percentile Method= 0
Sediment Output Level= 3
Mass or Volume Output= 0
Output Increment Type= 1
Profile and TS Output Increment= 1
Transport Output Increment 1
XS Output Flag= 0
XS Output Increment= 10
Read HDF5 Sediment Hotstart= 0
Sediment Hotstart Type= 0
Write Gradation File= 0
Read Gradation Hotstart= 0
Write HDF5 File= 1
Write Binary Output= 1
Write DSS Sediment File= 0
DSS Sediment Output Type= 1
SV Curve= 0
Specific Gage Flag= 0
Subcell Erosion Methods= 0
Subcell Deposition Methods= 0
Advection Scheme= 1
Matrix Solver= 0
Implicit Weighting Factor= 1
Maximum Outer Loop Convergence Iterations= 5
Convergence Maximum Absolute= 0.001
Convergence RMSE= 0.0001
Grain Fractions Max Abs Error= 0.001
Max Subgrid Regions= 1
Max Subgrid Length Scale= 3.402823E+38
Initial Layer Thickness= 3.402823E+38
Min Layer Thickness= 3.402823E+38
Max Layer Thickness= 3.402823E+38
Number of Layers= 5

--- MissOhioRiv.u01 (unsteady flow) ---

Flow Title=1985 Flood Event
Program Version=6.20
Use Restart= 0
Initial Flow Loc=Mississippi Riv ,Upper           ,43.7    ,121000
Initial Flow Loc=Mississippi Riv ,Lower           ,953.03  ,186000
Initial Flow Loc=Ohio River      ,Main Stem       ,17.39   ,65000
Boundary Location=Mississippi Riv ,Upper           ,43.7    ,        ,                ,                ,                ,                                ,
Interval=1HOUR
Flow Hydrograph= 0
Stage Hydrograph TW Check=0
DSS File=dss
DSS Path=/MISSISSIPPI RIVER/THEBES/FLOW/01JAN1984/1DAY/OBS/
Use DSS=True
Use Fixed Start Time=False
Is Critical Boundary=False
Boundary Location=Mississippi Riv ,Lower           ,922     ,        ,                ,                ,                ,                                ,
Interval=1DAY
Stage Hydrograph= 365
  272.03  271.83  272.43  272.63  272.33  272.33  272.63  272.63  272.63  272.53
  272.33  272.33  272.33  272.03  272.13  272.43  272.43  272.83  273.73  275.33
  276.63  279.43  282.73  284.53  284.53  284.13  284.23  283.73  283.03  282.63
  283.23  283.93  285.93  289.23  291.03  292.53  293.23  293.33  292.63  291.33
  289.83  288.73  288.53  289.03  289.63  289.73  289.73  289.23  287.43  285.93
  286.43  288.53  290.53  291.83  292.13  291.43  289.93  287.83  287.03  288.73
  291.43  292.93  293.33  293.23  292.83  292.03  290.83  288.73  287.03  285.63
  284.53  283.53  282.83  282.43  283.03  284.83  286.03  286.73  287.73  288.73
  289.43  290.13  293.43  295.43  296.53  297.33  297.83  298.03  297.93  297.63
  297.33  297.23  299.03  301.03  302.43  303.33  303.83  303.13  301.73  300.43
  299.43  298.63  297.93  297.23  296.03  293.83  291.63  289.93  287.93  286.13
  285.13  284.33  283.53  283.03  282.63  281.83  280.63  279.83  279.43  278.93
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Use DSS=False
Use Fixed Start Time=False
Is Critical Boundary=False
Critical Boundary Flow=0
Boundary Location=Ohio River      ,Main Stem       ,17.39   ,        ,                ,                ,                ,                                ,
Interval=1HOUR
Flow Hydrograph= 0
Stage Hydrograph TW Check=0
DSS File=DSS
DSS Path=/OHIO RIVER/L&D 53 TW/FLOW/01JAN1984/1DAY/OBS/
Use DSS=True
Use Fixed Start Time=False
Is Critical Boundary=False
Precipitation Mode=Disable
Wind Mode=No Wind Forces
Air Density Mode=Specified
Met BC=Precipitation|Expanded View=0
Met BC=Precipitation|Point Interpolation=Nearest
Met BC=Precipitation|Gridded Source=DSS
Met BC=Evapotranspiration|Expanded View=0
Met BC=Evapotranspiration|Point Interpolation=Nearest
Met BC=Evapotranspiration|Gridded Source=DSS
Met BC=Wind Speed|Expanded View=0
Met BC=Wind Speed|Point Interpolation=Nearest
Met BC=Wind Speed|Gridded Source=DSS
Met BC=Wind Direction|Expanded View=0
Met BC=Wind Direction|Point Interpolation=Nearest
Met BC=Wind Direction|Gridded Source=DSS
Met BC=Wind Velocity X|Expanded View=0
Met BC=Wind Velocity X|Point Interpolation=Nearest
Met BC=Wind Velocity X|Gridded Source=DSS
Met BC=Wind Velocity Y|Expanded View=0
Met BC=Wind Velocity Y|Point Interpolation=Nearest
Met BC=Wind Velocity Y|Gridded Source=DSS
Met BC=Air Density|Mode=Constant
Met BC=Air Density|Expanded View=0
Met BC=Air Density|Constant Value=1.225
Met BC=Air Density|Constant Units=kg/m3
Met BC=Air Density|Point Interpolation=Nearest
Met BC=Air Density|Gridded Source=DSS
Met BC=Air Temperature|Expanded View=0
Met BC=Air Temperature|Point Interpolation=Nearest
Met BC=Air Temperature|Gridded Source=DSS
Met BC=Humidity|Expanded View=0
Met BC=Humidity|Point Interpolation=Nearest
Met BC=Humidity|Gridded Source=DSS
Met BC=Air Pressure|Expanded View=0
Met BC=Air Pressure|Point Interpolation=Nearest
Met BC=Air Pressure|Gridded Source=DSS
Observed DSS Loc=Mississippi Riv ,Upper           ,43.7
Observed DSS Filename=DSS
Observed DSS Pathname=/MISSISSIPPI/THEBES/STAGE/01JAN1984/1DAY/OBS/
Observed DSS Dn Dist=0
Observed DSS Loc=Mississippi Riv ,Upper           ,20.2
Observed DSS Filename=DSS
Observed DSS Pathname=/MISSISSIPPI/THOMPSON LANDING/STAGE/01JAN1982/1DAY/OBS/
Observed DSS Dn Dist=0
Observed DSS Loc=Mississippi Riv ,Upper           ,1.4
Observed DSS Filename=DSS
Observed DSS Pathname=/MISSISSIPPI/BIRDS POINT/STAGE/01JAN1982/1DAY/OBS/
Observed DSS Dn Dist=0
Observed DSS Loc=Mississippi Riv ,Lower           ,953.03
Observed DSS Filename=DSS
Observed DSS Pathname=/MISSISSIPPI RIVER/CAIRO/STAGE/01JAN1982/1DAY/OBS/
Observed DSS Dn Dist=0
Observed DSS Loc=Mississippi Riv ,Lower           ,922
Observed DSS Filename=DSS
Observed DSS Pathname=/MISSISSIPPI RIVER/HICKMAN/STAGE/01JAN1982/1DAY/OBS/
Observed DSS Dn Dist=0
Observed DSS Loc=Ohio River      ,Main Stem       ,17.39
Observed DSS Filename=DSS
Observed DSS Pathname=/OHIO RIVER/L&D 53 TW/STAGE/01JAN1985/1DAY/OBS/
Observed DSS Dn Dist=0
Observed RRR Location=Mississippi Riv, Upper (43.7)
Observed RRR DS Distance=0
Observed RRR Location=Mississippi Riv, Upper (20.2)
Observed RRR DS Distance=0
Observed RRR Location=Mississippi Riv, Upper (1.4)
Observed RRR DS Distance=0
Observed RRR Location=Mississippi Riv, Lower (953.03)
Observed RRR DS Distance=0
Observed RRR Location=Mississippi Riv, Lower (922)
Observed RRR DS Distance=0
Observed RRR Location=Ohio River, Main Stem (17.39)
Observed RRR DS Distance=0
Observed Time Series=Stage|TS Name=XS: Mississippi Riv, Upper (43.7)
Observed Time Series=Stage|TS Used=-1
Observed Time Series=Stage|TS Source=DSS
Observed Time Series=Stage|TS DSS Filename=dss
Observed Time Series=Stage|TS DSS Pathname=/MISSISSIPPI/THEBES/STAGE/01JAN1984-01JAN1985/1DAY/OBS/
Observed Time Series=Stage|TS Table Mode=0
Observed Time Series=Stage|TS Table Use Fixed Start=0
Observed Time Series=Stage|TS Table StartDateTime=02Oct1984 00:00:00
Observed Time Series=Stage|TS Table Interval=1 Hour
Observed Time Series=Stage|TS Table Data Units=ft
Observed Time Series=Stage|TS Table Data Type=INST-VAL
Observed Time Series=Stage|TS Constant Units=ft
Observed Time Series=Stage|TS Name=XS: Mississippi Riv, Upper (20.2)
Observed Time Series=Stage|TS Used=-1
Observed Time Series=Stage|TS Source=DSS
Observed Time Series=Stage|TS DSS Filename=dss
Observed Time Series=Stage|TS DSS Pathname=/MISSISSIPPI/THOMPSON LANDING/STAGE/01JAN1982/1DAY/OBS/
Observed Time Series=Stage|TS Table Mode=0
Observed Time Series=Stage|TS Table Use Fixed Start=0
Observed Time Series=Stage|TS Table StartDateTime=02Oct1984 00:00:00
Observed Time Series=Stage|TS Table Interval=1 Hour
Observed Time Series=Stage|TS Table Data Units=ft
Observed Time Series=Stage|TS Table Data Type=INST-VAL
Observed Time Series=Stage|TS Constant Units=ft
Observed Time Series=Stage|TS Name=XS: Mississippi Riv, Upper (1.4)
Observed Time Series=Stage|TS Used=-1
Observed Time Series=Stage|TS Source=DSS
Observed Time Series=Stage|TS DSS Filename=dss
Observed Time Series=Stage|TS DSS Pathname=/MISSISSIPPI/BIRDS POINT/STAGE/01JAN1984-01JAN1985/1DAY/OBS/
Observed Time Series=Stage|TS Table Mode=0
Observed Time Series=Stage|TS Table Use Fixed Start=0
Observed Time Series=Stage|TS Table StartDateTime=02Oct1984 00:00:00
Observed Time Series=Stage|TS Table Interval=1 Hour
Observed Time Series=Stage|TS Table Data Units=ft
Observed Time Series=Stage|TS Table Data Type=INST-VAL
Observed Time Series=Stage|TS Constant Units=ft
Observed Time Series=Stage|TS Name=XS: Mississippi Riv, Lower (953.03)
Observed Time Series=Stage|TS Used=-1
Observed Time Series=Stage|TS Source=DSS
Observed Time Series=Stage|TS DSS Filename=dss
Observed Time Series=Stage|TS DSS Pathname=/MISSISSIPPI RIVER/CAIRO/STAGE/01JAN1982/1DAY/OBS/
Observed Time Series=Stage|TS Table Mode=0
Observed Time Series=Stage|TS Table Use Fixed Start=0
Observed Time Series=Stage|TS Table StartDateTime=02Oct1984 00:00:00
Observed Time Series=Stage|TS Table Interval=1 Hour
Observed Time Series=Stage|TS Table Data Units=ft
Observed Time Series=Stage|TS Table Data Type=INST-VAL
Observed Time Series=Stage|TS Constant Units=ft
Observed Time Series=Stage|TS Name=XS: Mississippi Riv, Lower (922)
Observed Time Series=Stage|TS Used=-1
Observed Time Series=Stage|TS Source=DSS
Observed Time Series=Stage|TS DSS Filename=dss
Observed Time Series=Stage|TS DSS Pathname=/MISSISSIPPI RIVER/HICKMAN/STAGE/01JAN1982/1DAY/OBS/
Observed Time Series=Stage|TS Table Mode=0
Observed Time Series=Stage|TS Table Use Fixed Start=0
Observed Time Series=Stage|TS Table StartDateTime=02Oct1984 00:00:00
Observed Time Series=Stage|TS Table Interval=1 Hour
Observed Time Series=Stage|TS Table Data Units=ft
Observed Time Series=Stage|TS Table Data Type=INST-VAL
Observed Time Series=Stage|TS Constant Units=ft
Observed Time Series=Stage|TS Name=XS: Ohio River, Main Stem (17.39)
Observed Time Series=Stage|TS Used=-1
Observed Time Series=Stage|TS Source=DSS
Observed Time Series=Stage|TS DSS Filename=dss
Observed Time Series=Stage|TS DSS Pathname=/OHIO RIVER/L&D 53 TW/STAGE/01JAN1985/1DAY/OBS/
Observed Time Series=Stage|TS Table Mode=0
Observed Time Series=Stage|TS Table Use Fixed Start=0
Observed Time Series=Stage|TS Table StartDateTime=02Oct1984 00:00:00
Observed Time Series=Stage|TS Table Interval=1 Hour
Observed Time Series=Stage|TS Table Data Units=ft
Observed Time Series=Stage|TS Table Data Type=INST-VAL
Observed Time Series=Stage|TS Constant Units=ft
Non-Newtonian Method= 0 ,
Non-Newtonian Constant Vol Conc=0
Non-Newtonian Yield Method= 0 ,
Non-Newtonian Yield Coef=0, 0
User Yeild=   0
Non-Newtonian Sed Visc= 0 ,
Non-Newtonian Obrian B=0
User Viscosity=0
User Viscosity Ratio=0
Herschel-Bulkley Coef=0, 0
Clastic Method= 0 ,
Coulomb Phi=0
Voellmy X=0
Non-Newtonian Hindered FV= 0
Non-Newtonian FV K=0
Non-Newtonian ds=0
Non-Newtonian Max Cv=0
Non-Newtonian Bulking Method= 0 ,
Non-Newtonian High C Transport= 0 ,
Lava Activation= 0
Temperature=1300,15,,15,14,980
Heat Ballance=1,1200,0.5,1,70,0.95
Viscosity=1000,,,
Profile Coefficient=4,1.3,
Lava Param=,2500,

--- MissOhioRiv.g01 (geometry) ---

Geom Title=Mississippi and Ohio River Geometry Data
Program Version=6.20

Junct Name=Confluence
Junct Desc=, 0 , 0 ,-1 ,0
Up River,Reach=Mississippi Riv ,Upper
Up River,Reach=Ohio River      ,Main Stem
Dn River,Reach=Mississippi Riv ,Lower
Junc L&A=1000,
Junc L&A=1000,

River Reach=Mississippi Riv ,Upper
Reach XY= 30
339090.958529667413805.415476618337228.645051274404245.350851762
342008.695750302395368.147985825367771.225663347394374.894518307
373358.276687468392202.152558113  374082.0143671  362381.7140248
  401967.2996662   316216.075019  417459.1248165  302583.2688696
  427488.2890871  286551.2417442  427138.2140768  268522.3787123
  433880.4578587  252389.7553196  459287.0461461  243404.4967211
  485932.9654741  225124.1430208  493988.6347064  233179.8921091
  497085.4026202  244334.0062313  490883.5617679  253938.9378366
  477540.1489842  258896.3218909  469712.4638487  265712.7249656
  467836.1911293  273458.6375505  472998.0404299  286026.1292288
  482864.3698222  290468.3811244  487919.6868628  289520.5091793
  495976.5983964  281463.5976457   508614.890998  260452.4361955
  524254.7780925  251605.6313744   531995.732311  238967.3387728
  534049.4548588  226960.9608012  538630.8359269   221747.665103
  552059.0218161  219535.9638978   567933.755803  226136.1414702

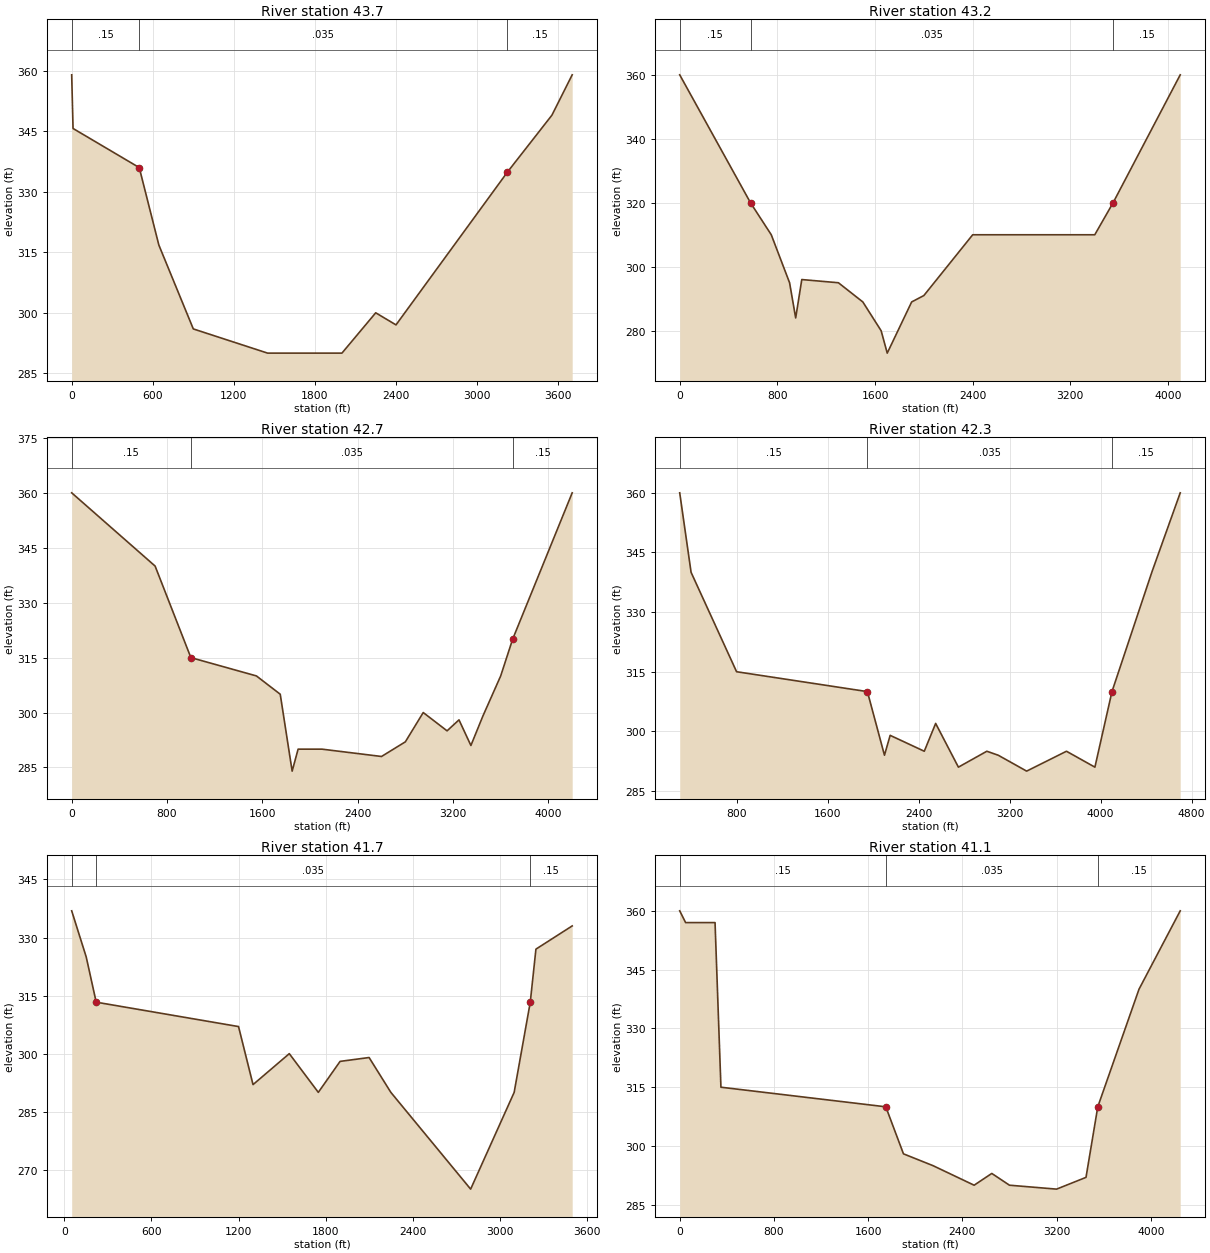
Type RM Length L Ch R = 1 ,43.7    ,2000,2640,2600
#Sta/Elev= 12
       0     359      10   345.7     500     336     645   316.8     900     296
    1450     290    2000     290    2250     300    2400     297    3225   334.9
    3554     349    3704     359
#Mann= 3 ,0,0
       0     .15       0     500    .035       0    3225     .15       0
Bank Sta=500,3225
XS Rating Curve= 0 ,0
Exp/Cntr=0.3,0.1

Type RM Length L Ch R = 1 ,43.2    ,3000,2640,3200
#Sta/Elev= 16
       0     360     580     320     750     310     900     295     950     284
    1000     296    1300     295    1500     289    1650     280    1700     273
    1900     289    2000     291    2400     310    3400     310    3550     320
    4100     360
#Mann= 3 ,0,0
       0     .15       0     580    .035       0    3550     .15       0
Bank Sta=580,3550
XS Rating Curve= 0 ,0
Exp/Cntr=0.3,0.1

Type RM Length L Ch R = 1 ,42.7    ,2600,2110,2400
#Sta/Elev= 18
       0     360     700     340    1000     315    1550     310    1750     305
    1850     284    1900     290    2100     290    2600     288    2800     292
    2950     300    3150     295    3250     298    3350     291    3450     299
    3600     310    3700     320    4200     360
#Mann= 3 ,0,0
       0     .15       0    1000    .035       0    3700     .15       0
Bank Sta=1000,3700
XS Rating Curve= 0 ,0
Exp/Cntr=0.3,0.1

Type RM Length L Ch R = 1 ,42.3    ,2050,3170,2900
#Sta/Elev= 17
     300     360     400     340     800     315    1950     310    2100     294
    2150     299    2450     295    2550     302    2750     291    3000     295
    3100     294    3350     290    3700     295    3950     291    4100     310
    4450     340    4700     360
#Mann= 3 ,0,0
     300     .15       0    1950    .035       0    4100     .15       0
Bank Sta=1950,4100
XS Rating Curve= 0 ,0
Exp/Cntr=0.3,0.1

Type RM Length L Ch R = 1 ,41.7    ,3150,3170,3200
#Sta/Elev= 15
      50   336.9     150     325     219   313.3    1200     307    1300     292
    1550     300    1750     290    1900     298    2100     299    2250     290
    2800     265    3100     290    3211   313.3    3250     327    3500     333
#Mann= 3 ,0,0
      50     .15       0     219    .035       0    3211     .15       0
Bank Sta=219,3211
XS Rating Curve= 0 ,0
Exp/Cntr=0.3,0.1

Type RM Length L Ch R = 1 ,41.1    ,2700,2640,2800
#Sta/Elev= 15
       0     360      50     357     300     357     350     315    1750     310
    1900     298    2150     295    2500     290    2650     293    2800     290
    3200     289    3450     292    3550     310    3900     340    4250     360
#Mann= 3 ,0,0
       0     .15       0    1750    .035       0    3550     .15       0
Bank Sta=1750,3550
XS Rating Curve= 0 ,0
Exp/Cntr=0.3,0.1

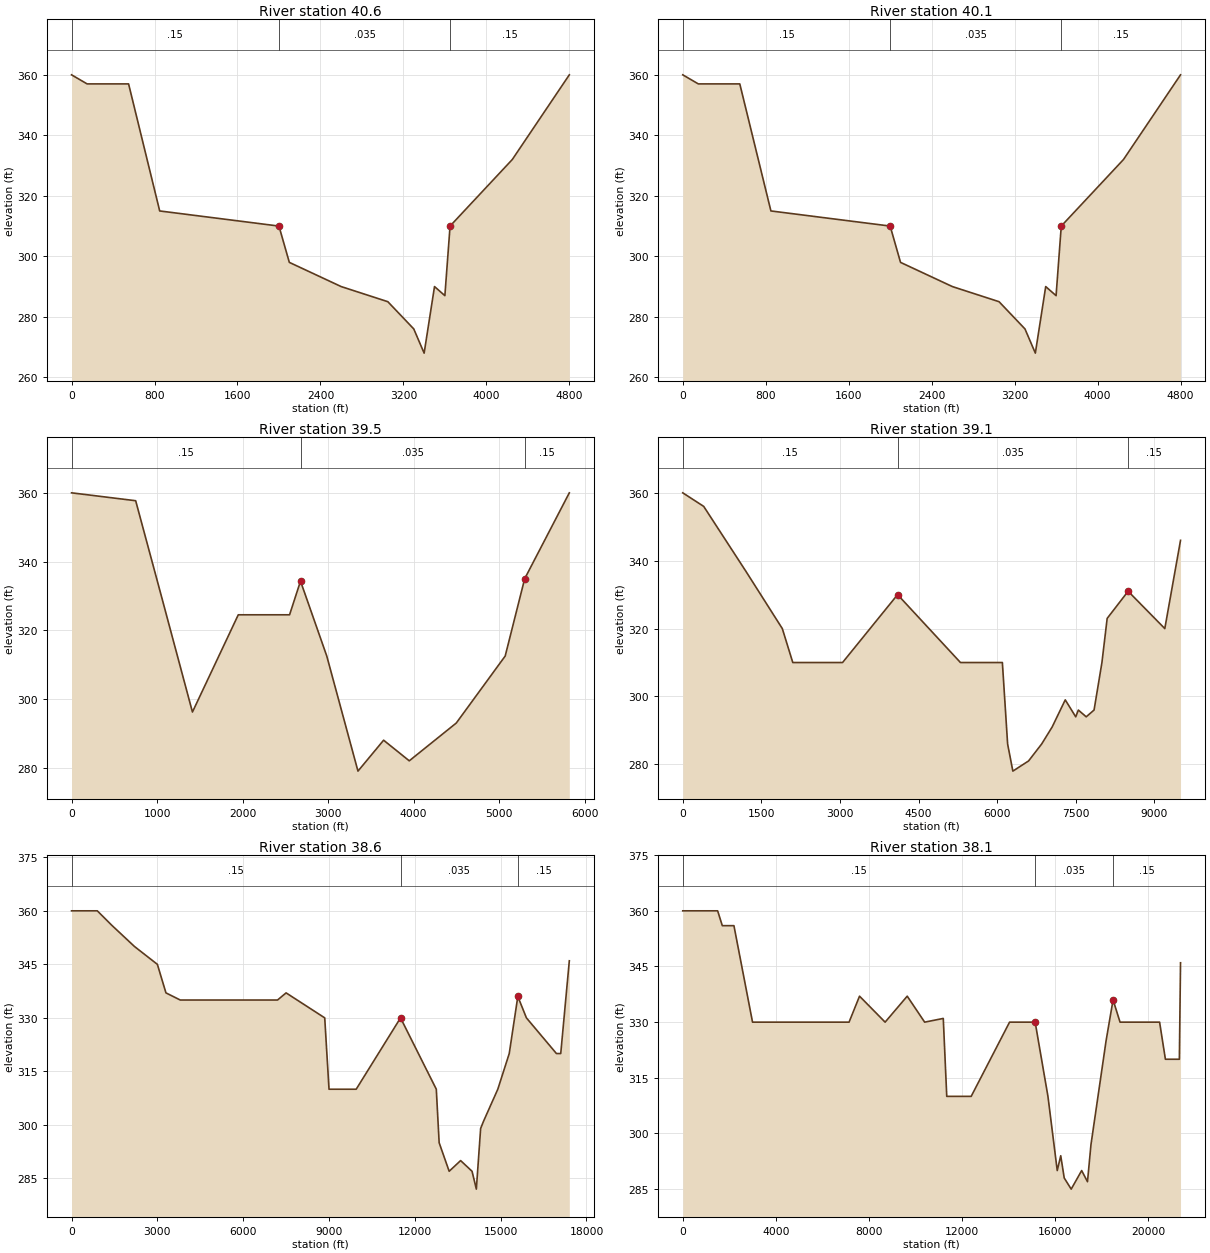
Type RM Length L Ch R = 1 ,40.6    ,2600,2640,2500
#Sta/Elev= 15
       0     360     150     357     550     357     850     315    2000     310
    2100     298    2600     290    3050     285    3300     276    3400     268
    3500     290    3600     287    3650     310    4250     332    4800     360
#Mann= 3 ,0,0
       0     .15       0    2000    .035       0    3650     .15       0
Bank Sta=2000,3650
XS Rating Curve= 0 ,0
Exp/Cntr=0.3,0.1

Type RM Length L Ch R = 1 ,40.1    ,2700,3170,2400
#Sta/Elev= 15
       0     360     150     357     550     357     850     315    2000     310
    2100     298    2600     290    3050     285    3300     276    3400     268
    3500     290    3600     287    3650     310    4250     332    4800     360
#Mann= 3 ,0,0
       0     .15       0    2000    .035       0    3650     .15       0
Bank Sta=2000,3650
XS Rating Curve= 0 ,0
Exp/Cntr=0.3,0.1

Type RM Length L Ch R = 1 ,39.5    ,3100,2110,2700
#Sta/Elev= 15
       0     360     750   357.7    1050     330    1414   296.2    1950   324.5
    2550   324.5    2678   334.3    2985   312.5    3350     279    3650     288
    3950     282    4500     293    5072   312.5    5300     335    5822     360
#Mann= 3 ,0,0
       0     .15       0    2678    .035       0    5300     .15       0
Bank Sta=2678,5300
XS Rating Curve= 0 ,0
Exp/Cntr=0.3,0.1

Type RM Length L Ch R = 1 ,39.1    ,2350,2640,3300
#Sta/Elev= 24
       0     360     400     356    1200     337    1900     320    2100     310
    3050     310    4100     330    5300     310    6100     310    6200     286
    6300     278    6600     281    6850     286    7050     291    7300     299
    7500     294    7550     296    7700     294    7850     296    8000     310
    8100     323    8500     331    9200     320    9500     346
#Mann= 3 ,0,0
       0     .15       0    4100    .035       0    8500     .15       0
Bank Sta=4100,8500
XS Rating Curve= 0 ,0
Exp/Cntr=0.3,0.1

Type RM Length L Ch R = 1 ,38.6    ,2450,2640,2500
#Sta/Elev= 29
       0     360     700     360     900     360    1400     356    2200     350
    3000     345    3300     337    3800     335    7200     335    7500     337
    8850     330    9000     310    9950     310   11500     330   12750     310
   12850     295   13200     287   13600     290   14000     287   14150     282
   14300     299   14400     301   14900     310   15300     320   15600     336
   15900     330   16950     320   17100     320   17400     346
#Mann= 3 ,0,0
       0     .15       0   11500    .035       0   15600     .15       0
Bank Sta=11500,15600
XS Rating Curve= 0 ,0
Exp/Cntr=0.3,0.1

Type RM Length L Ch R = 1 ,38.1    ,2450,2640,2500
#Sta/Elev= 30
       0     360    1500     360    1700     356    2200     356    3000     330
    7150     330    7600     337    8700     330    9650     337   10400     330
   11200     331   11350     310   12400     310   14050     330   15150     330
   15700     310   16100     290   16250     294   16400     288   16700     285
   17150     290   17400     287   17550     297   18200     325   18500     336
   18800     330   20500     330   20750     320   21350     320   21400     346
#Mann= 3 ,0,0
       0     .15       0   15150    .035       0   18500     .15       0
Bank Sta=15150,18500
XS Rating Curve= 0 ,0
Exp/Cntr=0.3,0.1

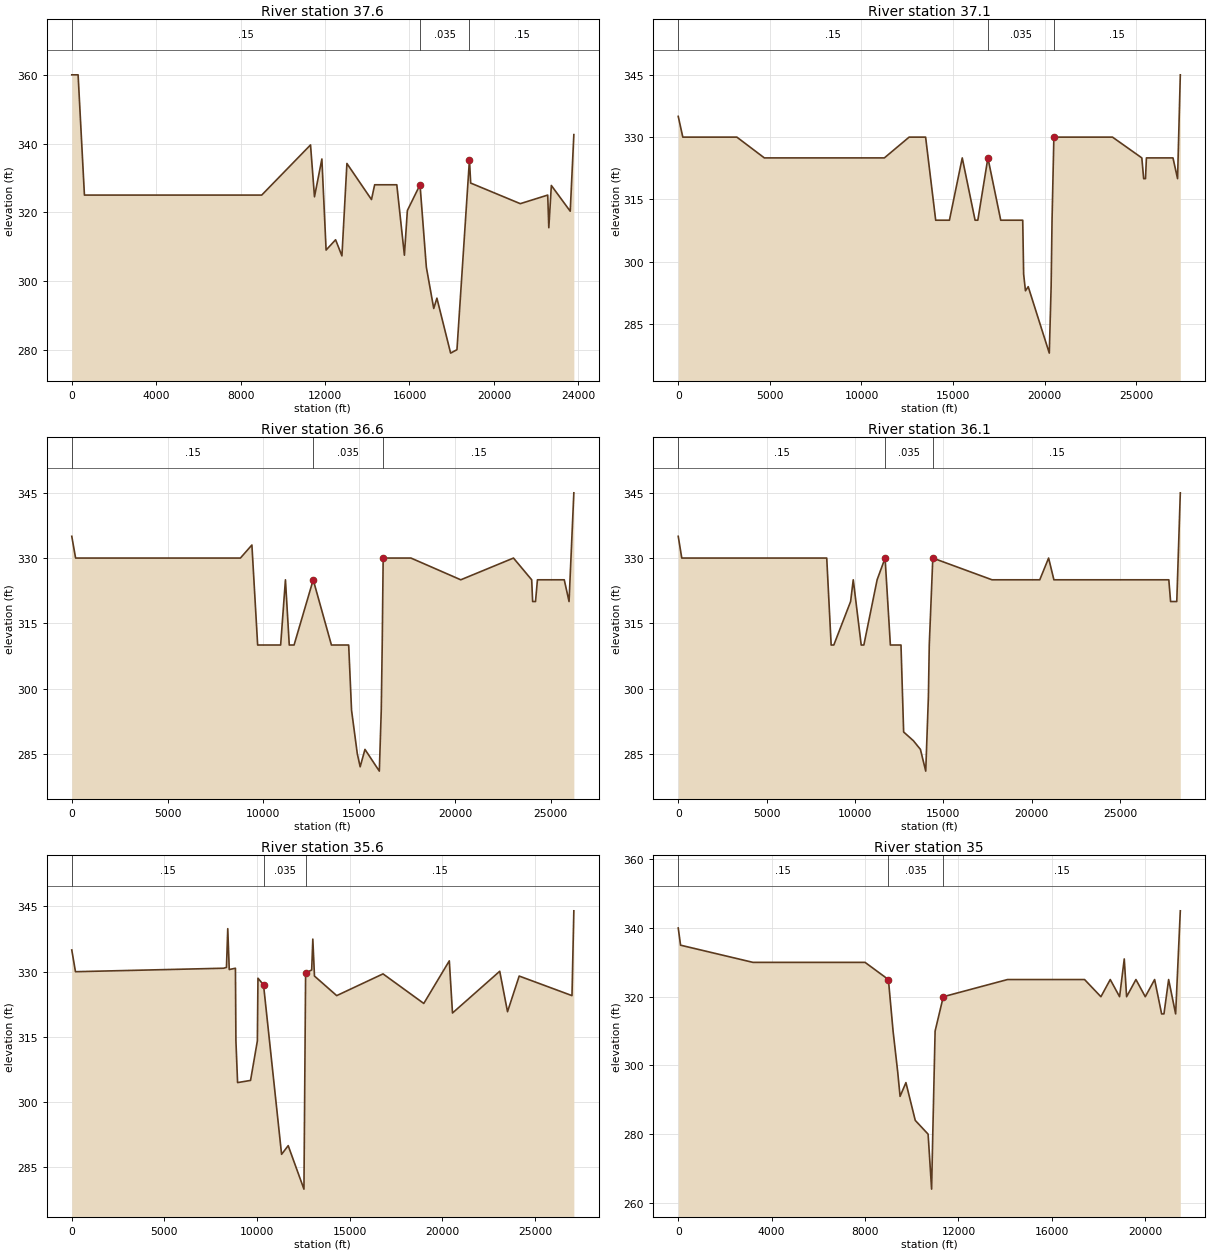
Type RM Length L Ch R = 1 ,37.6    ,2950,2640,2300
#Sta/Elev= 30
       0     360     300     360     600     325    9000     325   11312   339.6
   11500   324.5   11850   335.5   12050     309   12500     312   12800   307.3
   13036   334.2   14200   323.7   14350     328   15400     328   15760   307.5
   15900   320.5   16500     328   16800     304   17150     292   17300     295
   17950     279   18250     280   18842   335.3   18900   328.5   21250   322.5
   22550     325   22602   315.5   22722   327.8   23617   320.3   23788   342.6
#Mann= 3 ,0,0
       0     .15       0   16500    .035       0   18842     .15       0
Bank Sta=16500,18842
XS Rating Curve= 0 ,0
Exp/Cntr=0.3,0.1

Type RM Length L Ch R = 1 ,37.1    ,3450,2640,2650
#Sta/Elev= 30
       0     335     250     330    3200     330    4700     325   11250     325
   12600     330   13500     330   14050     310   14800     310   15500     325
   16200     310   16350     310   16900     325   17600     310   18800     310
   18850     297   18950     293   19100     294   20250     278   20350     294
   20400     310   20500     330   23700     330   25300     325   25400     320
   25500     320   25550     325   27000     325   27250     320   27400     345
#Mann= 3 ,0,0
       0     .15       0   16900    .035       0   20500     .15       0
Bank Sta=16900,20500
XS Rating Curve= 0 ,0
Exp/Cntr=0.3,0.1

Type RM Length L Ch R = 1 ,36.6    ,2250,2640,4300
#Sta/Elev= 30
       0     335     200     330    8800     330    9400     333    9700     310
   10900     310   11150     325   11350     310   11600     310   12600     325
   13550     310   14450     310   14600     295   14900     285   15050     282
   15300     286   16050     281   16150     295   16200     310   16250     330
   17700     330   20300     325   23050     330   24000     325   24050     320
   24200     320   24300     325   25700     325   25950     320   26200     345
#Mann= 3 ,0,0
       0     .15       0   12600    .035       0   16250     .15       0
Bank Sta=12600,16250
XS Rating Curve= 0 ,0
Exp/Cntr=0.3,0.1

Type RM Length L Ch R = 1 ,36.1    ,2300,2640,6250
#Sta/Elev= 28
       0     335     200     330    8400     330    8650     310    8800     310
    9750     320    9900     325   10350     310   10500     310   11250     325
   11700     330   12000     310   12600     310   12750     290   13300     288
   13700     286   14000     281   14150     298   14200     310   14400     330
   17750     325   20450     325   20950     330   21250     325   27750     325
   27850     320   28200     320   28400     345
#Mann= 3 ,0,0
       0     .15       0   11700    .035       0   14400     .15       0
Bank Sta=11700,14400
XS Rating Curve= 0 ,0
Exp/Cntr=0.3,0.1

Type RM Length L Ch R = 1 ,35.6    ,3150,3170,3000
#Sta/Elev= 30
       0     335     200     330    8200   330.8    8350     331    8420   339.9
    8500   330.5    8834   330.8    8860   314.1    8950   304.5    9650     305
   10018   314.1   10050   328.5   10350     327   11325     288   11682     290
   12532     280   12622   329.7   12950   330.4   13011   337.5   13100     329
   14300   324.5   16800   329.5   19000   322.7   20378   332.5   20550   320.5
   23100   330.1   23520   320.8   24150     329   27000   324.5   27100     344
#Mann= 3 ,0,0
       0     .15       0   10350    .035       0   12622     .15       0
Bank Sta=10350,12622
XS Rating Curve= 0 ,0
Exp/Cntr=0.3,0.1

Type RM Length L Ch R = 1 ,35      ,2700,2640,2250
#Sta/Elev= 30
       0     340     100     335    3200     330    8000     330    9000     325
    9200     310    9400     298    9500     291    9750     295   10150     284
   10700     280   10850     264   10900     280   11000     310   11350     320
   14100     325   17400     325   18100     320   18500     325   18900     320
   19100     331   19200     320   19600     325   20000     320   20400     325
   20700     315   20800     315   21000     325   21300     315   21500     345
#Mann= 3 ,0,0
       0     .15       0    9000    .035       0   11350     .15       0
Bank Sta=9000,11350
XS Rating Curve= 0 ,0
Exp/Cntr=0.3,0.1

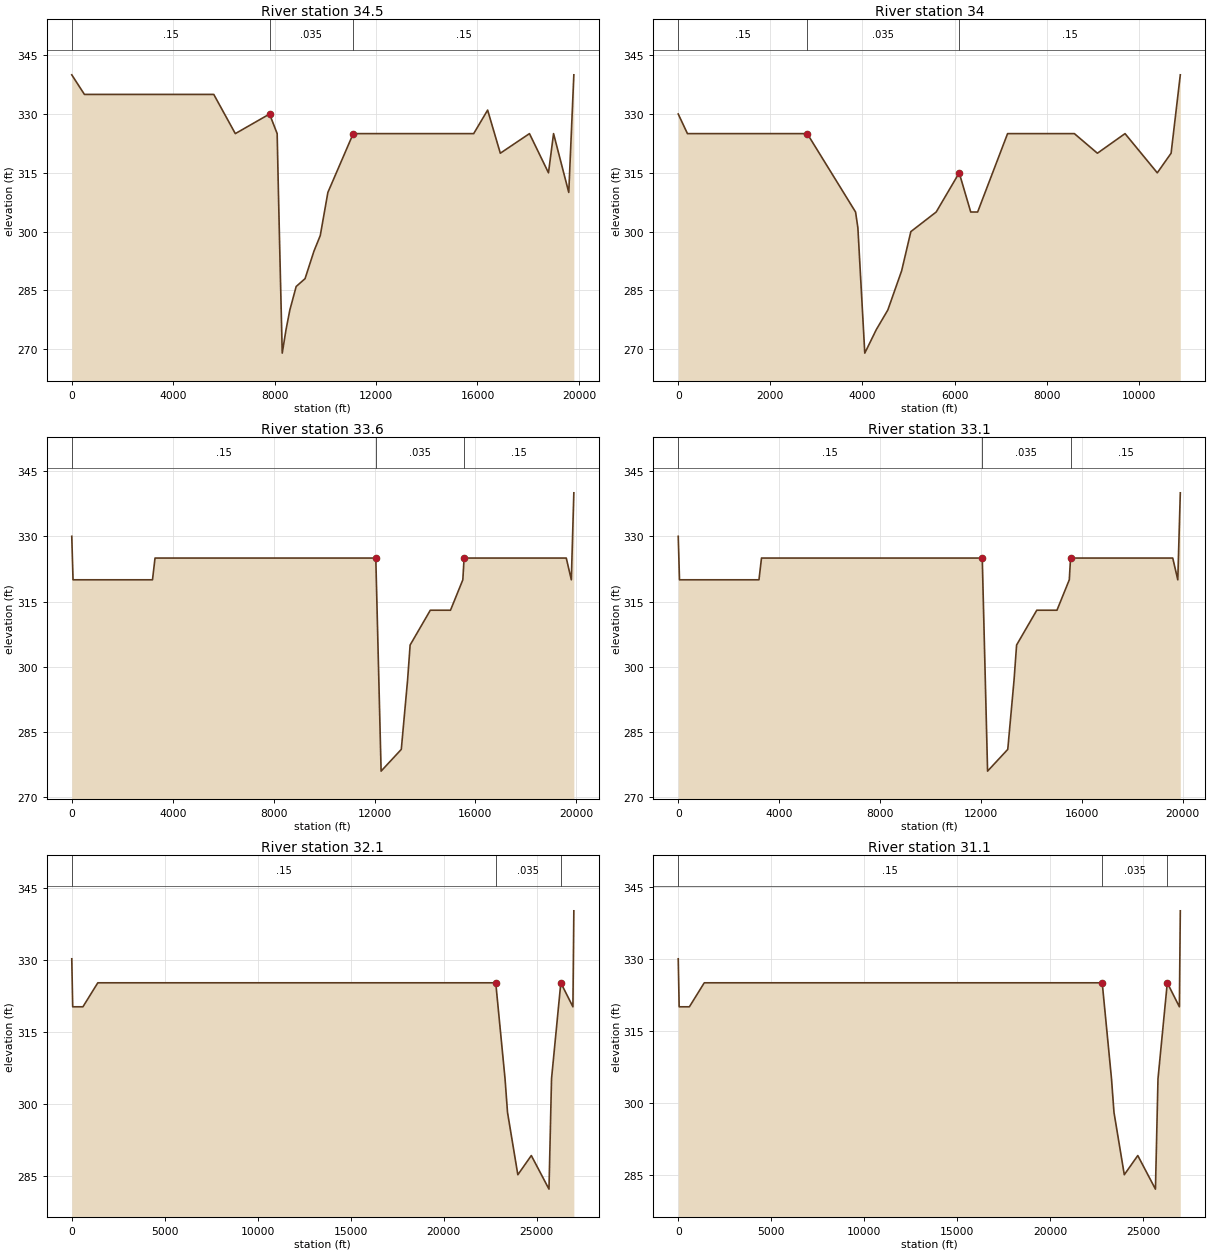
Type RM Length L Ch R = 1 ,34.5    ,3100,2640,1500
#Sta/Elev= 25
       0     340     500     335    5600     335    6450     325    7800     330
    8100     325    8150     310    8200     296    8300     269    8450     275
    8600     280    8850     286    9200     288    9550     295    9800     299
   10100     310   11100     325   15850     325   16400     331   16900     320
   18050     325   18800     315   19000     325   19600     310   19800     340
#Mann= 3 ,0,0
       0     .15       0    7800    .035       0   11100     .15       0
Bank Sta=7800,11100
XS Rating Curve= 0 ,0
Exp/Cntr=0.3,0.1

Type RM Length L Ch R = 1 ,34      ,2750,2120,1100
#Sta/Elev= 22
       0     330     200     325    2800     325    3850     305    3900     301
    4050     269    4300     275    4550     280    4700     285    4850     290
    5050     300    5600     305    6100     315    6350     305    6500     305
    7150     325    8600     325    9100     320    9700     325   10400     315
   10700     320   10900     340
#Mann= 3 ,0,0
       0     .15       0    2800    .035       0    6100     .15       0
Bank Sta=2800,6100
XS Rating Curve= 0 ,0
Exp/Cntr=0.3,0.1

Type RM Length L Ch R = 1 ,33.6    ,2750,2640,1100
#Sta/Elev= 16
       0     330      50     320    3200     320    3300     325   12050     325
   12261     276   13061     281   13311     297   13411     305   14211     313
   15011     313   15500     320   15550     325   19600     325   19800     320
   19900     340
#Mann= 3 ,0,0
       0     .15       0   12050    .035       0   15550     .15       0
Bank Sta=12050,15550
XS Rating Curve= 0 ,0
Exp/Cntr=0.3,0.1

Type RM Length L Ch R = 1 ,33.1    ,2850,5280,3925
#Sta/Elev= 16
       0     330      50     320    3200     320    3300     325   12050     325
   12261     276   13061     281   13311     297   13411     305   14211     313
   15011     313   15500     320   15550     325   19600     325   19800     320
   19900     340
#Mann= 3 ,0,0
       0     .15       0   12050    .035       0   15550     .15       0
Bank Sta=12050,15550
XS Rating Curve= 0 ,0
Exp/Cntr=0.3,0.1

Type RM Length L Ch R = 1 ,32.1    ,2850,5280,3925
#Sta/Elev= 14
       0   330.3      50   320.3     600   320.3    1400   325.3   22800   325.3
   23300   305.3   23433   298.3   23988   285.3   24713   289.3   25663   282.3
   25800   305.3   26300   325.3   26950   320.3   27000   340.3
#Mann= 3 ,0,0
       0     .15       0   22800    .035       0   26300     .15       0
Bank Sta=22800,26300
XS Rating Curve= 0 ,0
Exp/Cntr=0.3,0.1

Type RM Length L Ch R = 1 ,31.1    ,12500,2900,3025
#Sta/Elev= 14
       0     330      50     320     600     320    1400     325   22800     325
   23300     305   23433     298   23988     285   24713     289   25663     282
   25800     305   26300     325   26950     320   27000     340
#Mann= 3 ,0,0
       0     .15       0   22800    .035       0   26300     .15       0
Bank Sta=22800,26300
XS Rating Curve= 0 ,0
Exp/Cntr=0.3,0.1

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
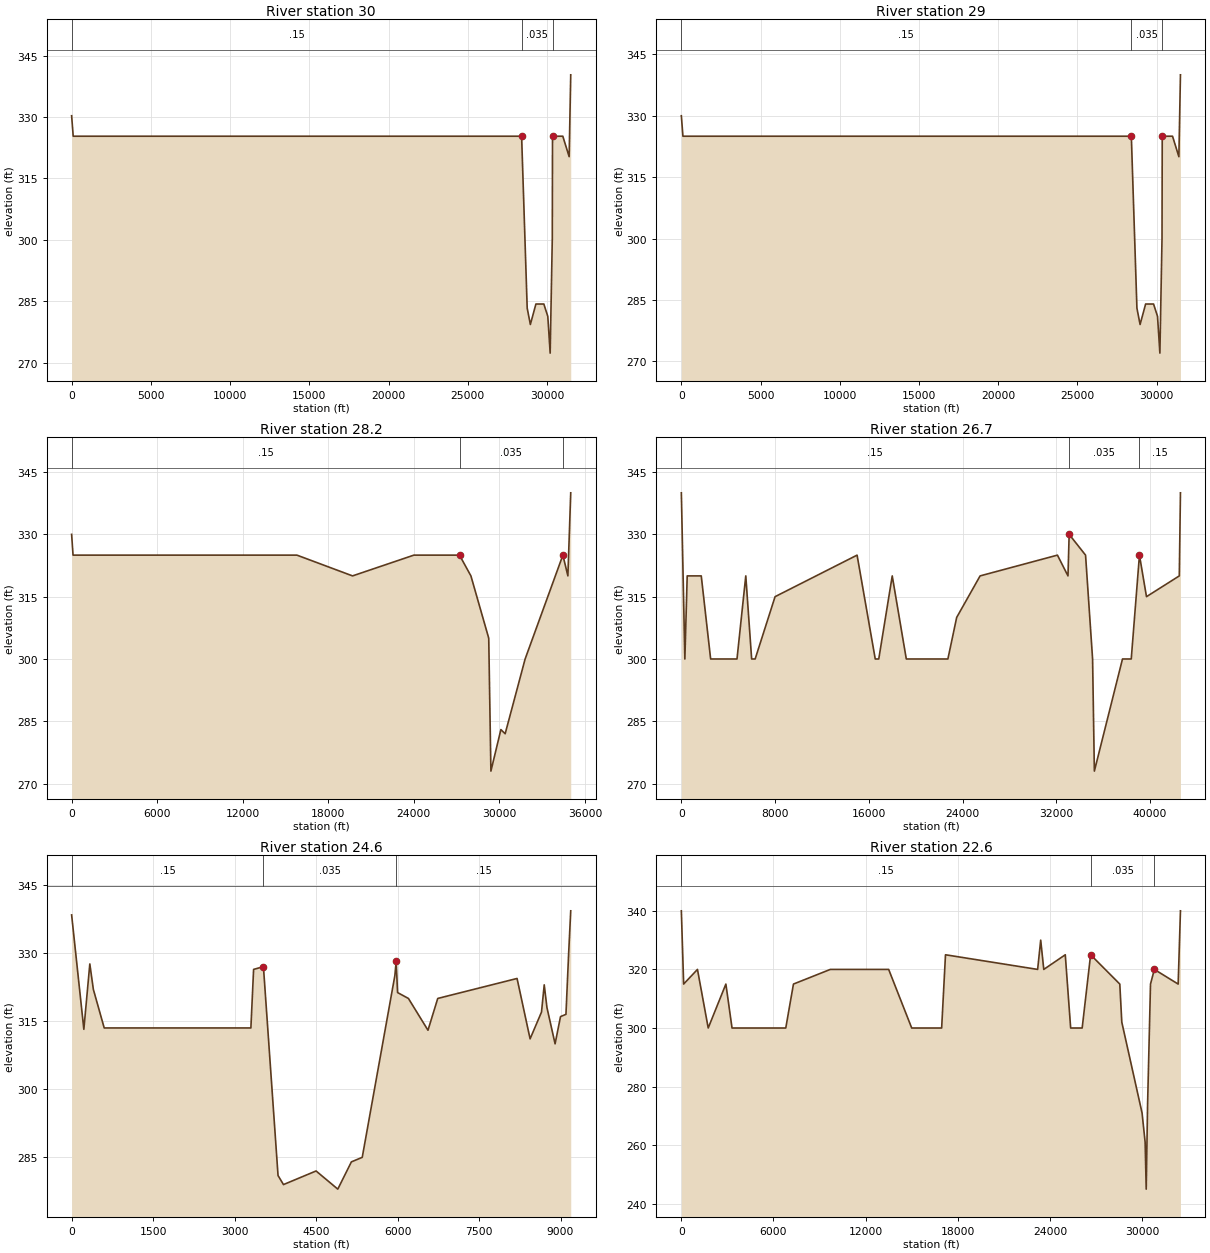
Type RM Length L Ch R = 1 ,30      ,2500,5280,6050
#Sta/Elev= 14
       0   330.3     100   325.3   28400   325.3   28752   283.3   28952   279.3
   29302   284.3   29802   284.3   30052   281.3   30202   272.3   30336   300.3
   30350   325.3   31000   325.3   31400   320.3   31500   340.3
#Mann= 3 ,0,0
       0     .15       0   28400    .035       0   30350     .15       0
Bank Sta=28400,30350
XS Rating Curve= 0 ,0
Exp/Cntr=0.3,0.1

Type RM Length L Ch R = 1 ,29      ,3700,4230,4200
#Sta/Elev= 14
       0     330     100     325   28400     325   28752     283   28952     279
   29302     284   29802     284   30052     281   30202     272   30336     300
   30350     325   31000     325   31400     320   31500     340
#Mann= 3 ,0,0
       0     .15       0   28400    .035       0   30350     .15       0
Bank Sta=28400,30350
XS Rating Curve= 0 ,0
Exp/Cntr=0.3,0.1

Type RM Length L Ch R = 1 ,28.2    ,3833.33,2640,2566.67
#Sta/Elev= 15
       0     330     100     325   15800     325   19700     320   24000     325
   27200     325   28000     320   29250     305   29402     273   30102     283
   30402     282   31802     300   34450     325   34800     320   35000     340
#Mann= 3 ,0,0
       0     .15       0   27200    .035       0   34450     .15       0
Bank Sta=27200,34450
XS Rating Curve= 0 ,0
Exp/Cntr=0.3,0.1

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
Type RM Length L Ch R = 1 ,26.7    ,3166.67,3696.67,3800
#Sta/Elev= 30
       0     340     300     300     500     320    1700     320    2500     300
    4750     300    5500     320    6000     300    6300     300    8000     315
   15000     325   16550     300   16850     300   18000     320   19200     300
   22750     300   23500     310   25500     320   32100     325   33000     320
   33100     330   34500     325   35100     300   35252     273   37652     300
   38400     300   39100     325   39700     315   42500     320   42600     340
#Mann= 3 ,0,0
       0     .15       0   33100    .035       0   39100     .15       0
Bank Sta=33100,39100
XS Rating Curve= 0 ,0
Exp/Cntr=0.3,0.1

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
Type RM Length L Ch R = 1 ,24.6    ,2650,5280,7075
#Sta/Elev= 30
       0   338.4     225   313.2     335   327.6     400     322     600   313.5
    3300   313.5    3350   326.4    3531     327    3800     281    3900     279
    4500     282    4900     278    5150     284    5350     285    5950     325
    5975   328.2    6000   321.3    6200     320    6560     313    6740     320
    8200   324.4    8440   311.1    8650     317    8700     323    8750     318
    8900     310    9000     316    9100   316.5    9150     330    9188   339.3
#Mann= 3 ,0,0
       0     .15       0    3531    .035       0    5975     .15       0
Bank Sta=3531,5975
XS Rating Curve= 0 ,0
Exp/Cntr=0.3,0.1

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
Type RM Length L Ch R = 1 ,22.6    ,2550,3695,3850
#Sta/Elev= 30
       0     340     150     315    1050     320    1750     300    2900     315
    3300     300    6800     300    7300     315    9700     320   13500     320
   15000     300   16950     300   17200     325   23200     320   23400     330
   23600     320   25000     325   25350     300   26100     300   26650     325
   28550     315   28680     302   30000     271   30200     261   30270     245
   30360     274   30550     315   30800     320   32350     315   32500     340
#Mann= 3 ,0,0
       0     .15       0   26650    .035       0   30800     .15       0
Bank Sta=26650,30800
XS Rating Curve= 0 ,0
Exp/Cntr=0.3,0.1

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