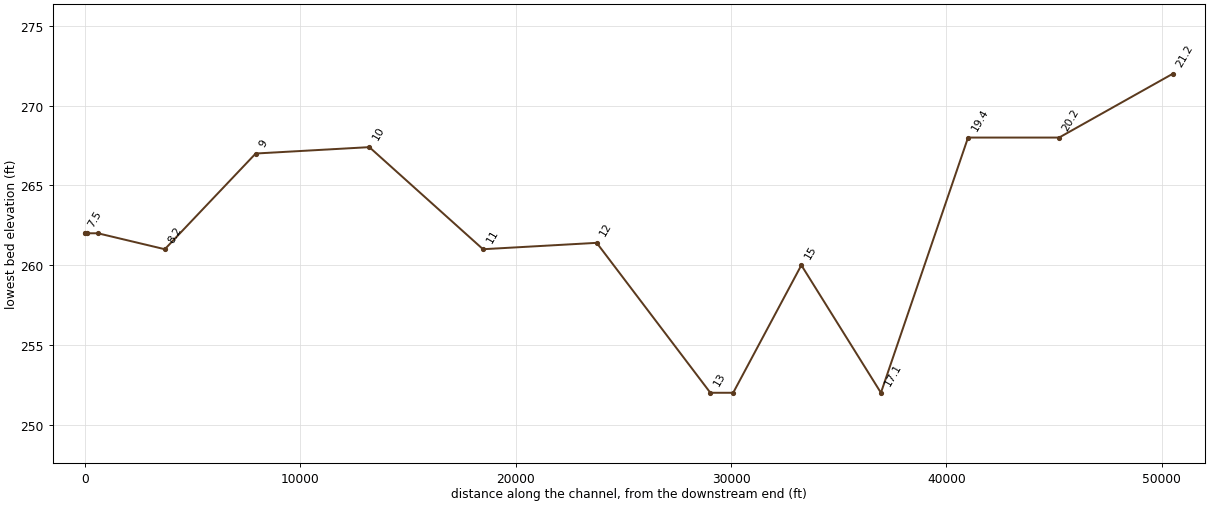
HEC-RAS study MissOhioRiv.prj: Mississippi - Ohio River System

--- MissOhioRiv.g01 (geometry) --- (continued)

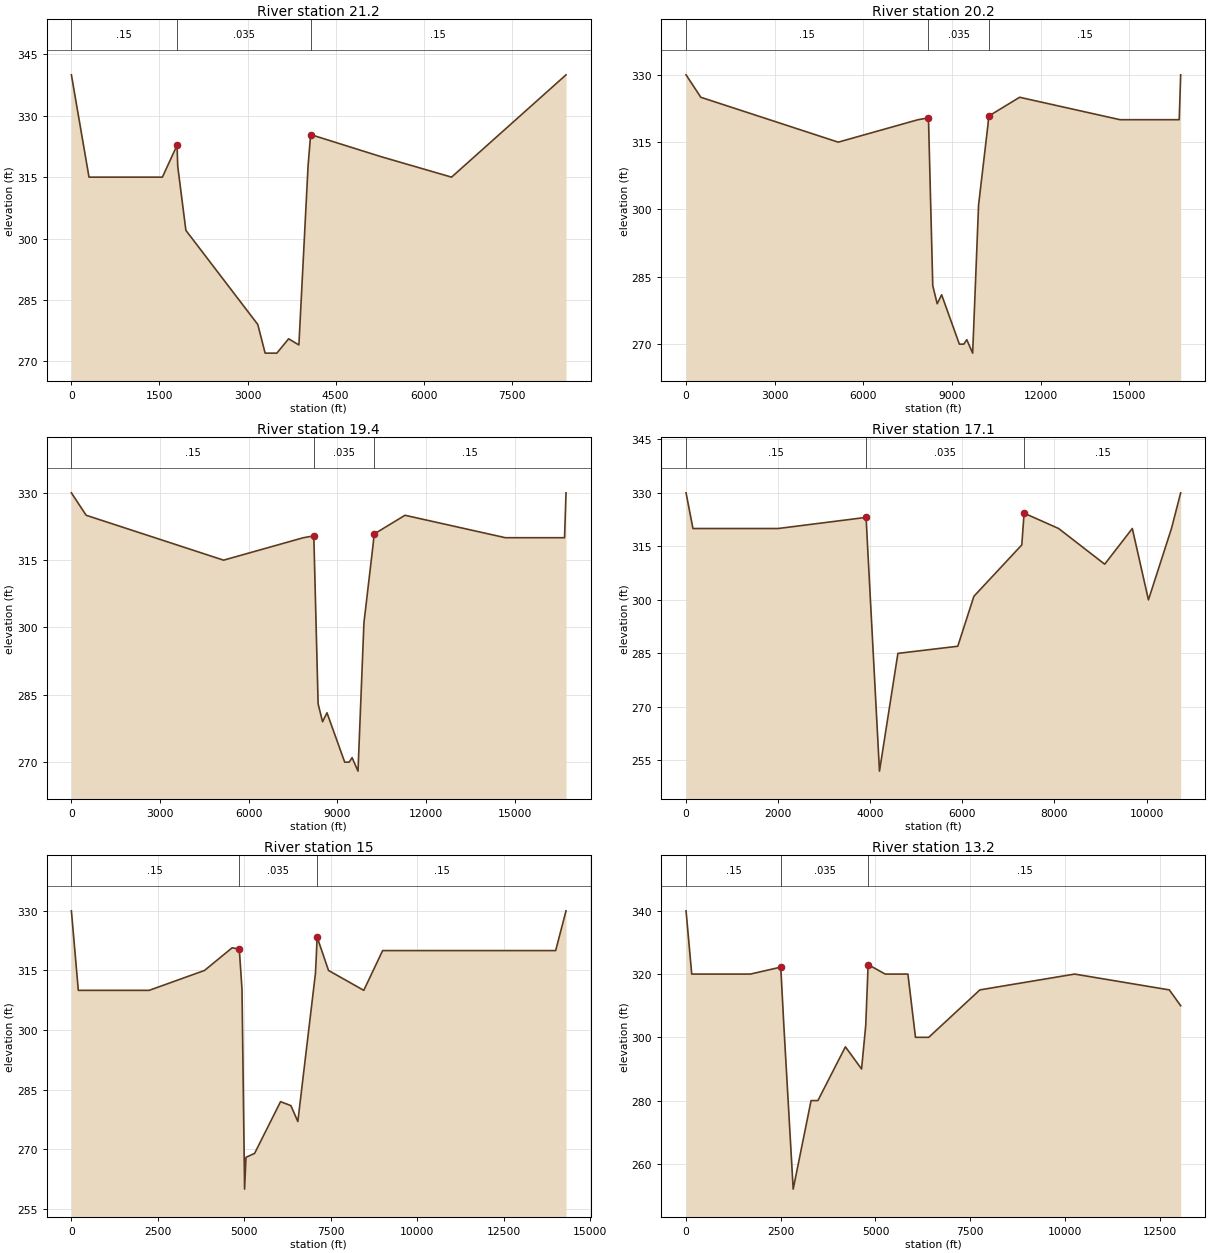
Type RM Length L Ch R = 1 ,21.2    ,5280,5280,5280
#Sta/Elev= 16
       0     340     300     315    1550     315    1800   322.8    1811   317.7
    1950     302    3175     279    3300     272    3500     272    3700   275.5
    3875     274    4031   317.7    4075   325.4    5275     320    6475     315
    8425     340
#Mann= 3 ,0,0
       0     .15       0    1800    .035       0    4075     .15       0
Bank Sta=1800,4075
XS Rating Curve= 0 ,0
Exp/Cntr=0.3,0.1

Type RM Length L Ch R = 1 ,20.2    ,4230,4230,4230
#Sta/Elev= 20
       0     330     500     325    5150     315    7850     320    8200   320.4
    8210     319    8350     283    8500     279    8650     281    9250     270
    9400     270    9500     271    9700     268    9900     301   10220     319
   10240   320.8   11290     325   14690     320   16690     320   16740     330
#Mann= 3 ,0,0
       0     .15       0    8200    .035       0   10240     .15       0
Bank Sta=8200,10240
XS Rating Curve= 0 ,0
Exp/Cntr=0.3,0.1

Type RM Length L Ch R = 1 ,19.4    ,4046.67,4046.67,4046.67
#Sta/Elev= 20
       0     330     500     325    5150     315    7850     320    8200   320.4
    8210     319    8350     283    8500     279    8650     281    9250     270
    9400     270    9500     271    9700     268    9900     301   10220     319
   10240   320.8   11290     325   14690     320   16690     320   16740     330
#Mann= 3 ,0,0
       0     .15       0    8200    .035       0   10240     .15       0
Bank Sta=8200,10240
XS Rating Curve= 0 ,0
Exp/Cntr=0.3,0.1

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
Type RM Length L Ch R = 1 ,17.1    ,3696.67,3696.67,3696.67
#Sta/Elev= 18
       0     330     150     320    2000     320    3900   323.1    3911   322.7
    3940   315.4    4200     252    4600     285    5900     287    6250     301
    7290   315.4    7340   324.3    8090     320    9090     310    9690     320
   10040     300   10540     320   10740     330
#Mann= 3 ,0,0
       0     .15       0    3900    .035       0    7340     .15       0
Bank Sta=3900,7340
XS Rating Curve= 0 ,0
Exp/Cntr=0.3,0.1

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
Type RM Length L Ch R = 1 ,15      ,3166.67,3166.67,3166.67
#Sta/Elev= 22
       0     330     200     310    2250     310    3850     315    4650   320.7
    4856   320.4    4904   314.3    4935   310.2    5010     260    5050     268
    5300     269    6050     282    6350     281    6550     277    7060   314.3
    7088   319.3    7108   323.4    7438     315    8458     310    9003     320
   14008     320   14308     330
#Mann= 3 ,0,0
       0     .15       0    4856    .035       0    7108     .15       0
Bank Sta=4856,7108
XS Rating Curve= 0 ,0
Exp/Cntr=0.3,0.1

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
Type RM Length L Ch R = 1 ,13.2    ,1060,1060,1060
#Sta/Elev= 20
       0     340     150     320    1700     320    2500   322.2    2581   303.8
    2828     252    3300     280    3480     280    4206     297    4633     290
    4743   303.8    4806     323    5256     320    5856     320    6056     300
    6406     300    7756     315   10256     320   12756     315   13056     310
#Mann= 3 ,0,0
       0     .15       0    2500    .035       0    4806     .15       0
Bank Sta=2500,4806
XS Rating Curve= 0 ,0
Exp/Cntr=0.3,0.1

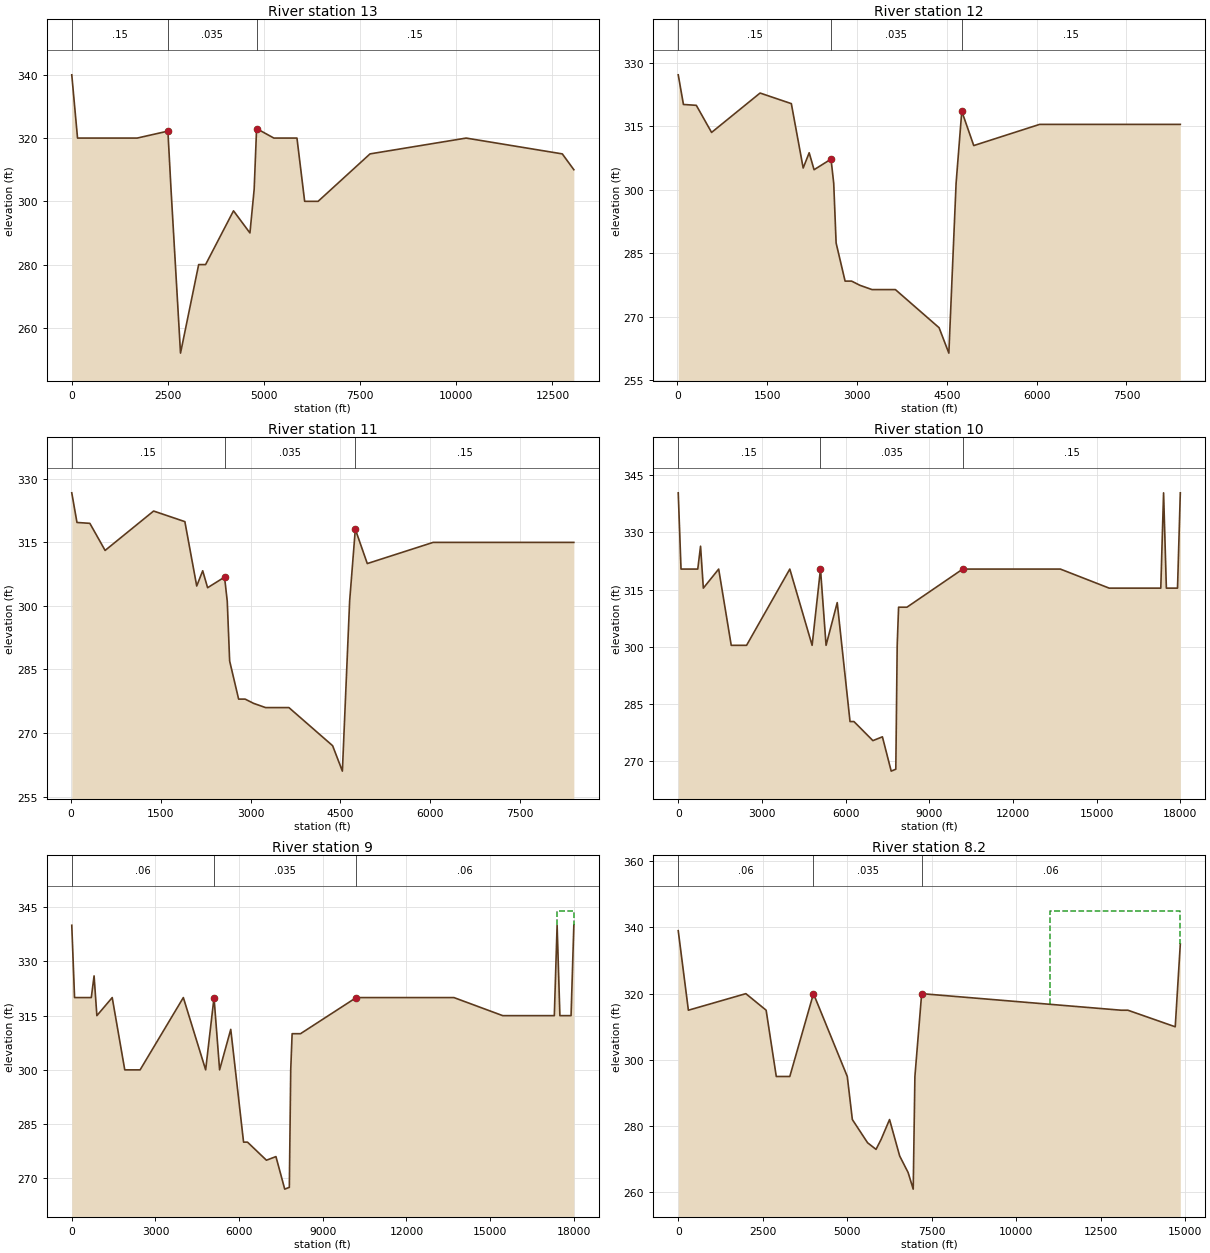
Type RM Length L Ch R = 1 ,13      ,5280,5280,5280
#Sta/Elev= 20
       0     340     150     320    1700     320    2500   322.2    2581   303.8
    2828     252    3300     280    3480     280    4206     297    4633     290
    4743   303.8    4806     323    5256     320    5856     320    6056     300
    6406     300    7756     315   10256     320   12756     315   13056     310
#Mann= 3 ,0,0
       0     .15       0    2500    .035       0    4806     .15       0
Bank Sta=2500,4806
XS Rating Curve= 0 ,0
Exp/Cntr=0.3,0.1

Type RM Length L Ch R = 1 ,12      ,5280,5280,5280
#Sta/Elev= 24
      13   327.1     100   320.1     315   319.9     570   313.5    1380   322.8
    1902   320.3    2100   305.1    2200   308.7    2282   304.7    2565   307.2
    2610   301.5    2650   287.4    2800   278.4    2909   278.4    3050   277.4
    3250   276.4    3640   276.4    4370   267.4    4533   261.4    4654   301.5
    4749   318.5    4949   310.4    6049   315.4    8399   315.4
#Mann= 3 ,0,0
      13     .15       0    2565    .035       0    4749     .15       0
Bank Sta=2565,4749
XS Rating Curve= 0 ,0
Exp/Cntr=0.3,0.1

Type RM Length L Ch R = 1 ,11      ,5280,5280,5280
#Sta/Elev= 24
      13   326.7     100   319.7     315   319.5     570   313.1    1380   322.4
    1902   319.9    2100   304.7    2200   308.3    2282   304.3    2565   306.8
    2610   301.1    2650     287    2800     278    2909     278    3050     277
    3250     276    3640     276    4370     267    4533     261    4654   301.1
    4749   318.1    4949     310    6049     315    8399     315
#Mann= 3 ,0,0
      13     .15       0    2565    .035       0    4749     .15       0
Bank Sta=2565,4749
XS Rating Curve= 0 ,0
Exp/Cntr=0.3,0.1

Type RM Length L Ch R = 1 ,10      ,5280,5280,5280
#Sta/Elev= 30
       0   340.4     100   320.4     700   320.4     800   326.4     900   315.4
    1450   320.4    1900   300.4    2450   300.4    4000   320.4    4800   300.4
    5100   320.4    5300   300.4    5700   311.6    6159   280.4    6300   280.4
    6979   275.4    7320   276.4    7635   267.4    7800   267.9    7850   300.4
    7900   310.4    8200   310.4   10200   320.4   13700   320.4   15450   315.4
   17300   315.4   17400   340.4   17500   315.4   17900   315.4   18000   340.4
#Mann= 3 ,0,0
       0     .15       0    5100    .035       0   10200     .15       0
Bank Sta=5100,10200
XS Rating Curve= 0 ,0
Exp/Cntr=0.3,0.1

Type RM Length L Ch R = 1 ,9       ,3850,4220,5000
#Sta/Elev= 30
       0     340     100     320     700     320     800     326     900     315
    1450     320    1900     300    2450     300    4000     320    4800     300
    5100     320    5300     300    5700   311.2    6159     280    6300     280
    6979     275    7320     276    7635     267    7800   267.5    7850     300
    7900     310    8200     310   10200     320   13700     320   15450     315
   17300     315   17400     340   17500     315   17900     315   18000     340
#Mann= 3 ,0,0
       0     .06       0    5100    .035       0   10200     .06       0
#XS Ineff= 1 ,-1
   17400   18000     344
Permanent Ineff=
       T
Bank Sta=5100,10200
XS Rating Curve= 0 ,0
Exp/Cntr=0.3,0.1

Type RM Length L Ch R = 1 ,8.2     ,1950,3110,2100
#Sta/Elev= 23
       0     339     300     315    2000     320    2600     315    2900     295
    3300     295    4000     320    4800     300    5000     295    5150     282
    5600     275    5850     273    6000     276    6250     282    6550     271
    6800     266    6950     261    7000     295    7200     320   13100     315
   13300     315   14700     310   14850     335
#Mann= 3 ,0,0
       0     .06       0    4000    .035       0    7200     .06       0
#XS Ineff= 1 ,-1
   11000   14850     345
Permanent Ineff=
       T
Bank Sta=4000,7200
XS Rating Curve= 0 ,0
Exp/Cntr=0.3,0.1

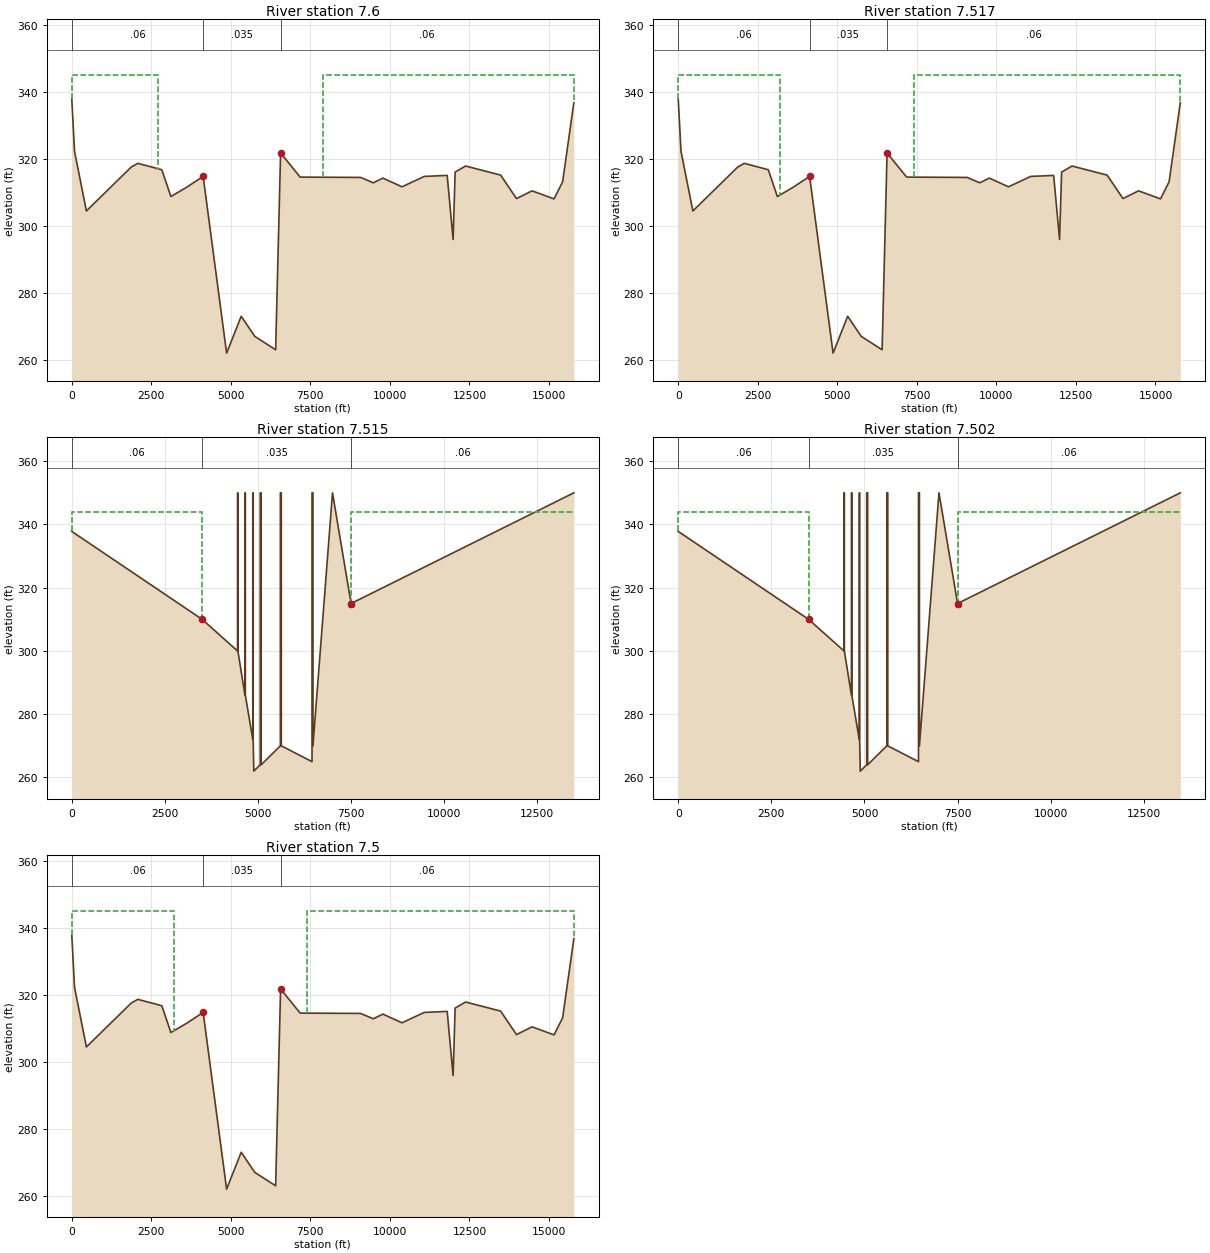
Type RM Length L Ch R = 1 ,7.6     ,500,500,500
#Sta/Elev= 30
       0   337.8      87   322.2     460   304.4    1870   317.5    2075   318.6
    2830   316.7    3116   308.7    3600   311.4    4130   314.7    4867     262
    5326     273    5752     267    6408     263    6564   321.7    7179   314.5
    9079   314.4    9479   312.8    9779   314.2   10379   311.6   11079   314.7
   11800     315   11986   295.9   12050     316   12379   317.8   13479   315.1
   13979   308.1   14469   310.4   15159     308   15429   313.1   15781   336.7
#Mann= 3 ,0,0
       0     .06       0    4130    .035       0    6564     .06       0
#XS Ineff= 2 ,-1
       0    2700     345    7900   15781     345
Permanent Ineff=
       T       T
Bank Sta=4130,6564
XS Rating Curve= 0 ,0
Exp/Cntr=0.3,0.1

Type RM Length L Ch R = 1 ,7.517   ,10,10,10
#Sta/Elev= 30
       0   337.8      87   322.2     460   304.4    1870   317.5    2075   318.6
    2830   316.7    3116   308.7    3600   311.4    4130   314.7    4867     262
    5326     273    5752     267    6408     263    6564   321.7    7179   314.5
    9079   314.4    9479   312.8    9779   314.2   10379   311.6   11079   314.7
   11800     315   11986   295.9   12050     316   12379   317.8   13479   315.1
   13979   308.1   14469   310.4   15159     308   15429   313.1   15781   336.7
#Mann= 3 ,0,0
       0     .06       0    4130    .035       0    6564     .06       0
#XS Ineff= 2 ,-1
       0    3200     345    7400   15781     345
Permanent Ineff=
       T       T
Bank Sta=4130,6564
XS Rating Curve= 0 ,0
Exp/Cntr=0.3,0.1

Type RM Length L Ch R = 1 ,7.515   ,70,70,70
#Sta/Elev= 30
       0   337.8    3499     310    4450     300    4450     350    4460     350
    4460     300    4650     286    4650     350    4660     350    4660     286
    4860     272    4860     350    4870     350    4870     272    4887     262
    5060     264    5060     350    5085     350    5085     264    5600     270
    5600     350    5625     350    5625     270    6450     265    6450     350
    6475     350    6475     270    7000     350    7499     315   13479     350
#Mann= 3 ,0,0
       0     .06       0    3499    .035       0    7499     .06       0
#XS Ineff= 2 , 0
            3499     344    7499             344
Permanent Ineff=
       T       T
Bank Sta=3499,7499
XS Rating Curve= 0 ,0
Exp/Cntr=0.3,0.1

Type RM Length L Ch R = 1 ,7.502   ,10,10,10
#Sta/Elev= 30
       0   337.8    3499     310    4450     300    4450     350    4460     350
    4460     300    4650     286    4650     350    4660     350    4660     286
    4860     272    4860     350    4870     350    4870     272    4887     262
    5060     264    5060     350    5085     350    5085     264    5600     270
    5600     350    5625     350    5625     270    6450     265    6450     350
    6475     350    6475     270    7000     350    7499     315   13479     350
#Mann= 3 ,0,0
       0     .06       0    3499    .035       0    7499     .06       0
#XS Ineff= 2 , 0
            3499     344    7499             344
Permanent Ineff=
       T       T
Bank Sta=3499,7499
XS Rating Curve= 0 ,0
Exp/Cntr=0.3,0.1

Type RM Length L Ch R = 1 ,7.5     ,4600,3170,1750
#Sta/Elev= 30
       0   337.8      87   322.2     460   304.4    1870   317.5    2075   318.6
    2830   316.7    3116   308.7    3600   311.4    4130   314.7    4867     262
    5326     273    5752     267    6408     263    6564   321.7    7179   314.5
    9079   314.4    9479   312.8    9779   314.2   10379   311.6   11079   314.7
   11800     315   11986   295.9   12050     316   12379   317.8   13479   315.1
   13979   308.1   14469   310.4   15159     308   15429   313.1   15781   336.7
#Mann= 3 ,0,0
       0     .06       0    4130    .035       0    6564     .06       0
#XS Ineff= 2 ,-1
       0    3200     345    7400   15781     345
Permanent Ineff=
       T       T
Bank Sta=4130,6564
XS Rating Curve= 0 ,0
Exp/Cntr=0.3,0.1