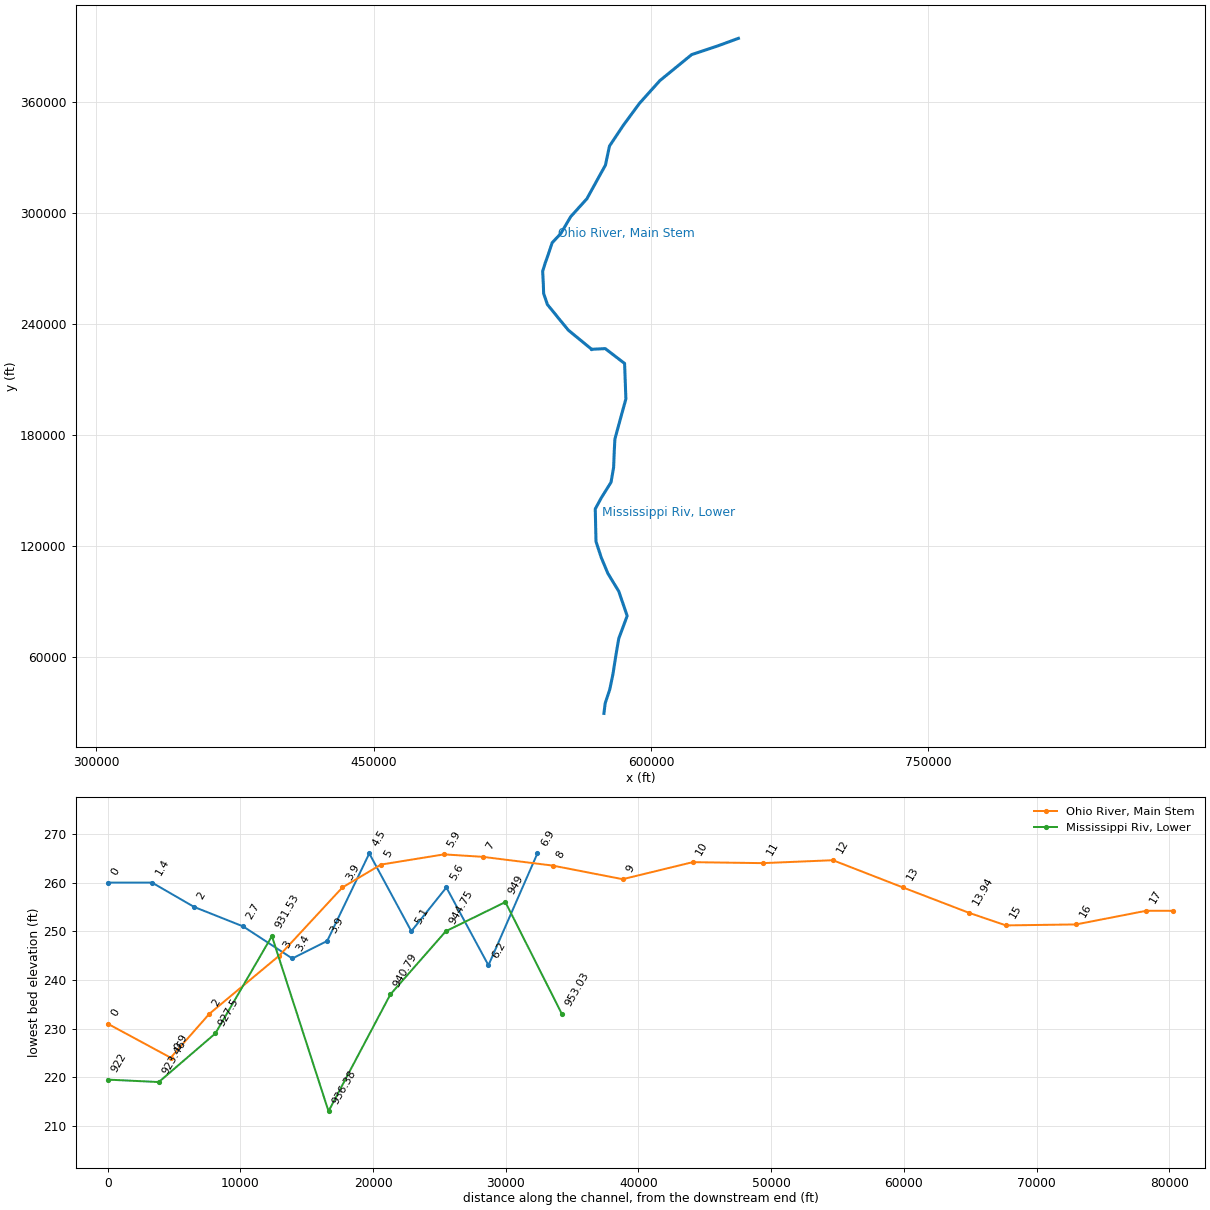
HEC-RAS study MissOhioRiv.prj: Mississippi - Ohio River System

--- MissOhioRiv.g01 (geometry) --- (continued)

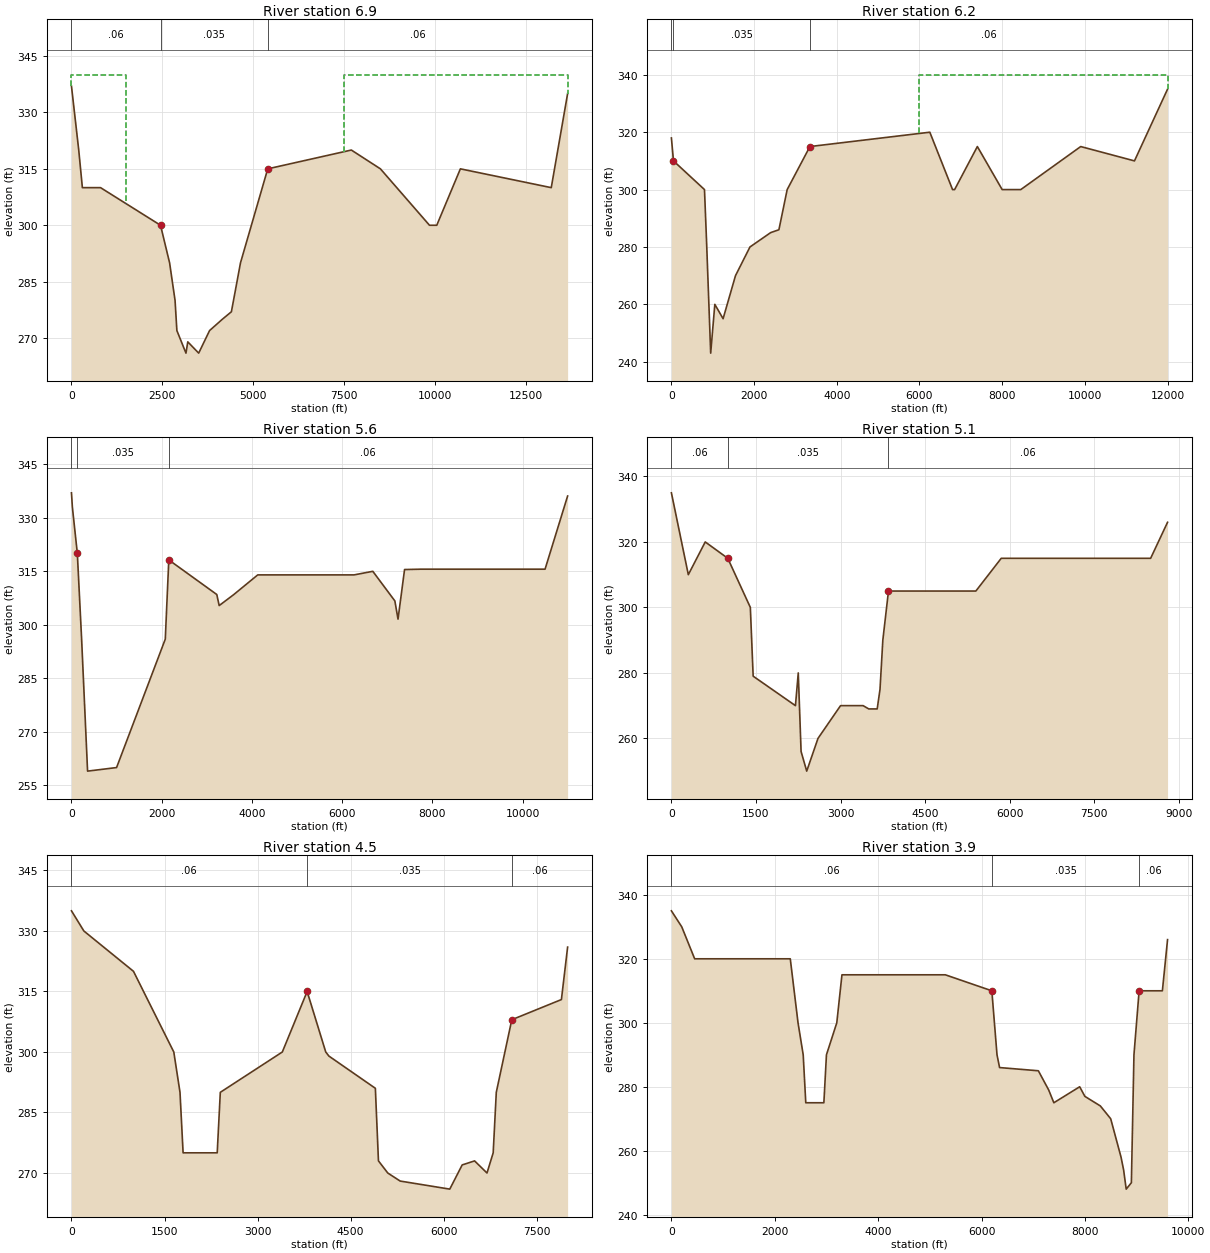
Type RM Length L Ch R = 1 ,6.9     ,3500,3690,2250
#Sta/Elev= 23
       0     337     200     320     300     310     800     310    2450     300
    2700     290    2850     280    2900     272    3150     266    3200     269
    3500     266    3800     272    4150     275    4400     277    4650     290
    5400     315    7700     320    8500     315    9850     300   10050     300
   10700     315   13200     310   13650     335
#Mann= 3 ,0,0
       0     .06       0    2450    .035       0    5400     .06       0
#XS Ineff= 2 ,-1
       0    1500     340    7500   13650     340
Permanent Ineff=
       T       T
Bank Sta=2450,5400
XS Rating Curve= 0 ,0
Exp/Cntr=0.3,0.1

Type RM Length L Ch R = 1 ,6.2     ,3200,3170,2200
#Sta/Elev= 23
       0     318      50     310     800     300     850     282     950     243
    1050     260    1250     255    1350     260    1550     270    1900     280
    2400     285    2600     286    2800     300    3350     315    6250     320
    6800     300    6850     300    7400     315    8000     300    8450     300
    9900     315   11200     310   12000     335
#Mann= 3 ,0,0
       0     .06       0      50    .035       0    3350     .06       0
#XS Ineff= 1 ,-1
    6000   12000     340
Permanent Ineff=
       T
Bank Sta=50,3350
XS Rating Curve= 0 ,0
Exp/Cntr=0.3,0.1

Type RM Length L Ch R = 1 ,5.6     ,2250,2640,3100
#Sta/Elev= 23
       0     337       5     336      10     335      15     334      20     333
     130     320     225     296     357     259    1000     260    2080     296
    2158   318.2    3222   308.5    3275   305.4    3590   308.4    4130     314
    6266     314    6681     315    7170   306.7    7240   301.6    7385   315.5
    7750   315.6   10500   315.6   11000   336.1
#Mann= 3 ,0,0
       0     .06       0     130    .035       0    2158     .06       0
Bank Sta=130,2158
XS Rating Curve= 0 ,0
Exp/Cntr=0.3,0.1

Type RM Length L Ch R = 1 ,5.1     ,2350,3170,3350
#Sta/Elev= 22
       0     335     300     310     600     320    1000     315    1400     300
    1450     279    2200     270    2250     280    2300     256    2400     250
    2600     260    3000     270    3400     270    3500     269    3650     269
    3700     275    3750     290    3850     305    5400     305    5850     315
    8500     315    8800     326
#Mann= 3 ,0,0
       0     .06       0    1000    .035       0    3850     .06       0
Bank Sta=1000,3850
XS Rating Curve= 0 ,0
Exp/Cntr=0.3,0.1

Type RM Length L Ch R = 1 ,4.5     ,1500,3170,3750
#Sta/Elev= 25
       0     335     200     330    1000     320    1650     300    1750     290
    1800     275    2350     275    2400     290    3400     300    3800     315
    4100     300    4150     299    4900     291    4950     273    5100     270
    5300     268    6100     266    6300     272    6500     273    6700     270
    6800     275    6850     290    7100     308    7900     313    8000     326
#Mann= 3 ,0,0
       0     .06       0    3800    .035       0    7100     .06       0
Bank Sta=3800,7100
XS Rating Curve= 0 ,0
Exp/Cntr=0.3,0.1

Type RM Length L Ch R = 1 ,3.9     ,1950,2630,3350
#Sta/Elev= 30
       0     335     200     330     450     320    2300     320    2450     300
    2550     290    2600     275    2950     275    3000     290    3200     300
    3300     315    5300     315    6200     310    6300     290    6350     286
    7100     285    7300     279    7400     275    7900     280    8000     277
    8300     274    8500     270    8700     258    8750     254    8800     248
    8900     250    8950     290    9050     310    9500     310    9600     326
#Mann= 3 ,0,0
       0     .06       0    6200    .035       0    9050     .06       0
Bank Sta=6200,9050
XS Rating Curve= 0 ,0
Exp/Cntr=0.3,0.1

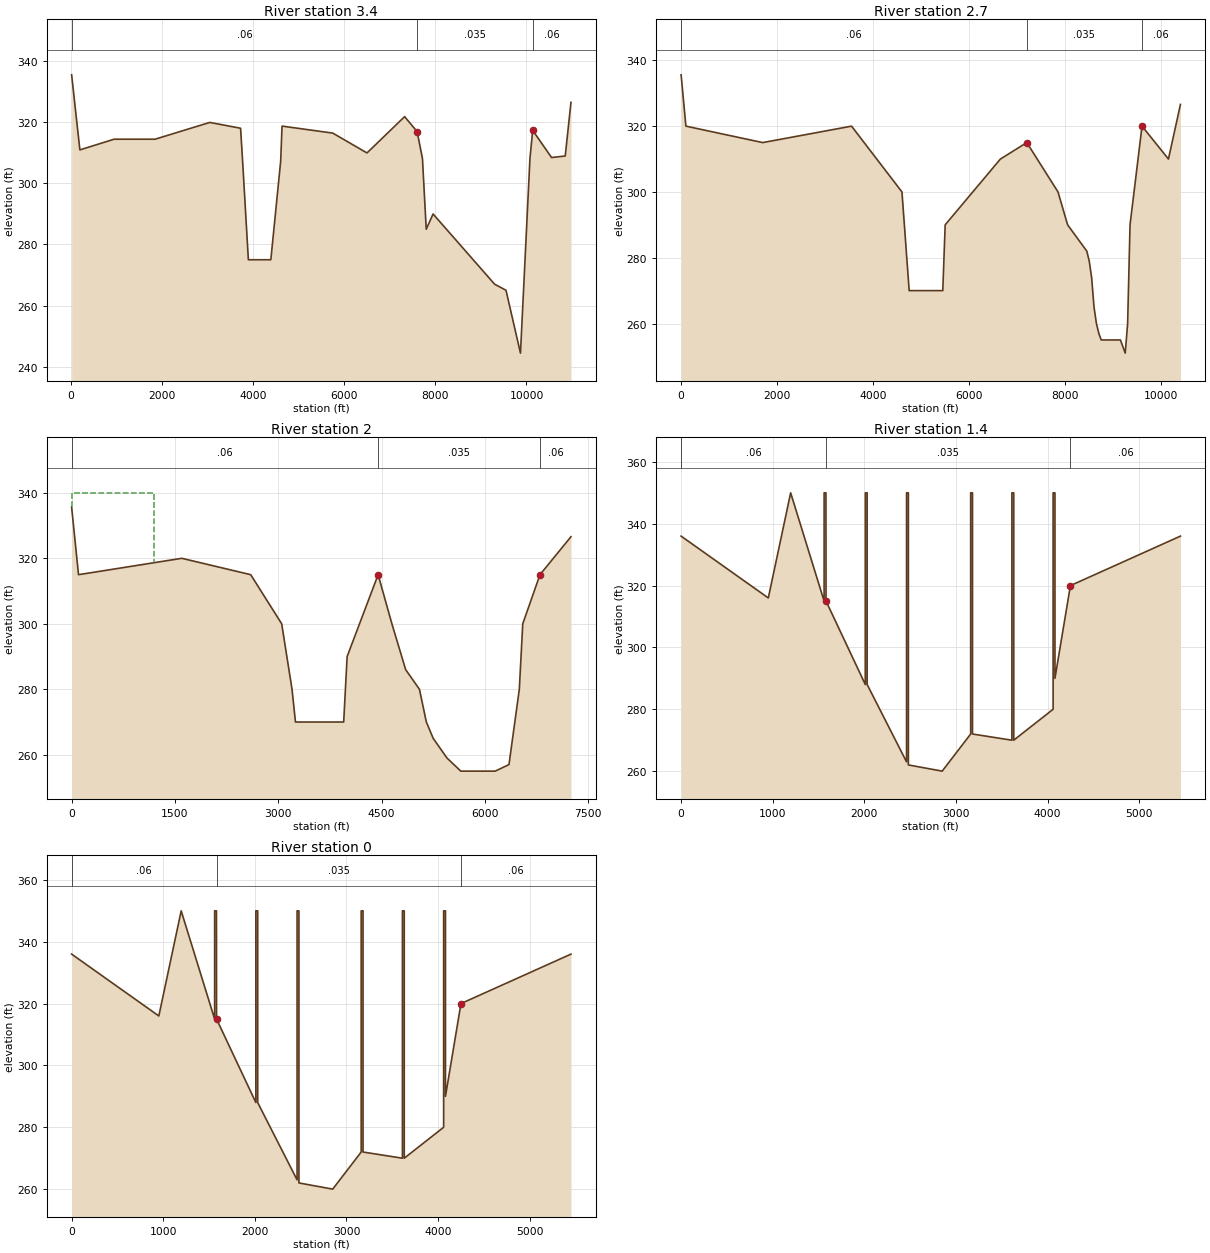
Type RM Length L Ch R = 1 ,3.4     ,3000,3710,5000
#Sta/Elev= 26
      19   335.6     200     311     950   314.5    1850   314.5    3050     320
    3726   318.1    3771   307.3    3897     275    4390     275    4606   307.3
    4636   318.8    5750   316.5    6500     310    7326   321.9    7600     317
    7717   308.2    7800     285    7950     290    9300     267    9550     265
    9868   244.4   10076   308.2   10136   317.4   10550   308.5   10850     309
   10976   326.6
#Mann= 3 ,0,0
      19     .06       0    7600    .035       0   10136     .06       0
Bank Sta=7600,10136
XS Rating Curve= 0 ,0
Exp/Cntr=0.3,0.1

Type RM Length L Ch R = 1 ,2.7     ,2050,3690,4150
#Sta/Elev= 28
       0   335.6     100     320    1700     315    3550     320    4600     300
    4700     280    4750     270    5450     270    5500     290    6650     310
    7200     315    7850     300    7950     295    8050     290    8450     282
    8500     279    8550     274    8600     265    8650     260    8700     257
    8750     255    9150     255    9250     251    9300     260    9350     290
    9600     320   10150     310   10400   326.6
#Mann= 3 ,0,0
       0     .06       0    7200    .035       0    9600     .06       0
Bank Sta=7200,9600
XS Rating Curve= 0 ,0
Exp/Cntr=0.3,0.1

Type RM Length L Ch R = 1 ,2       ,1450,3170,2550
#Sta/Elev= 23
       0   335.6     100     315    1600     320    2600     315    3050     300
    3200     280    3250     270    3950     270    4000     290    4450     315
    4650     300    4850     286    5050     280    5150     270    5250     265
    5450     259    5650     255    6150     255    6350     257    6500     280
    6550     300    6800     315    7250   326.6
#Mann= 3 ,0,0
       0     .06       0    4450    .035       0    6800     .06       0
#XS Ineff= 2 , 0
            1200     340
Permanent Ineff=
       T       T
Bank Sta=4450,6800
XS Rating Curve= 0 ,0
Exp/Cntr=0.3,0.1

Type RM Length L Ch R = 1 ,1.4     ,3344,3344,3344
#Sta/Elev= 30
       0     336     952     316    1196     350    1561     315    1561     350
    1581     350    1582     315    2011     288    2011     350    2031     350
    2031     288    2461     263    2461     350    2481     350    2481     262
    2850     260    3161     272    3161     350    3181     350    3181     272
    3611     270    3611     350    3631     350    3631     270    4061     280
    4061     350    4081     350    4081     290    4250     320    5451     336
#Mann= 3 ,0,0
       0     .06       0    1582    .035       0    4250     .06       0
Bank Sta=1582,4250
XS Rating Curve= 0 ,0
Exp/Cntr=0.3,0.1

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
Type RM Length L Ch R = 1 ,0       ,7392,7392,7392
#Sta/Elev= 30
       0     336     952     316    1196     350    1561     315    1561     350
    1581     350    1582     315    2011     288    2011     350    2031     350
    2031     288    2461     263    2461     350    2481     350    2481     262
    2850     260    3161     272    3161     350    3181     350    3181     272
    3611     270    3611     350    3631     350    3631     270    4061     280
    4061     350    4081     350    4081     290    4250     320    5451     336
#Mann= 3 ,0,0
       0     .06       0    1582    .035       0    4250     .06       0
Bank Sta=1582,4250
XS Rating Curve= 0 ,0
Exp/Cntr=0.3,0.1

River Reach=Ohio River      ,Main Stem
Reach XY= 24
   647280.067627  394274.7546211  636090.1694405  390177.9106428
   622007.072028  385483.5448386  604794.3974128  371400.4474261
   593840.877203  359195.0963353  585078.0610353  347302.7029648
  577567.0757486  336036.2250348  575376.3717067  325708.6202656
  572246.7945039  320075.3813006  565361.7246578  307557.0724895
    556598.90849  297855.3831609  551278.6272453  288779.6092728
  546584.2614411  283772.2857484  544238.3066676  276749.1411785
  542828.7687978  272818.7655387   541437.706585  268347.3409306
  541787.7815953  261695.9157343  541962.8191005  256269.7530742
  543013.0441315  253294.1154864  544002.1102826  250341.8021142
  548350.7470639  245026.8016037  549839.5068329  243141.9401868
  555376.5736241  236439.6802524   567933.755803  226136.1414702

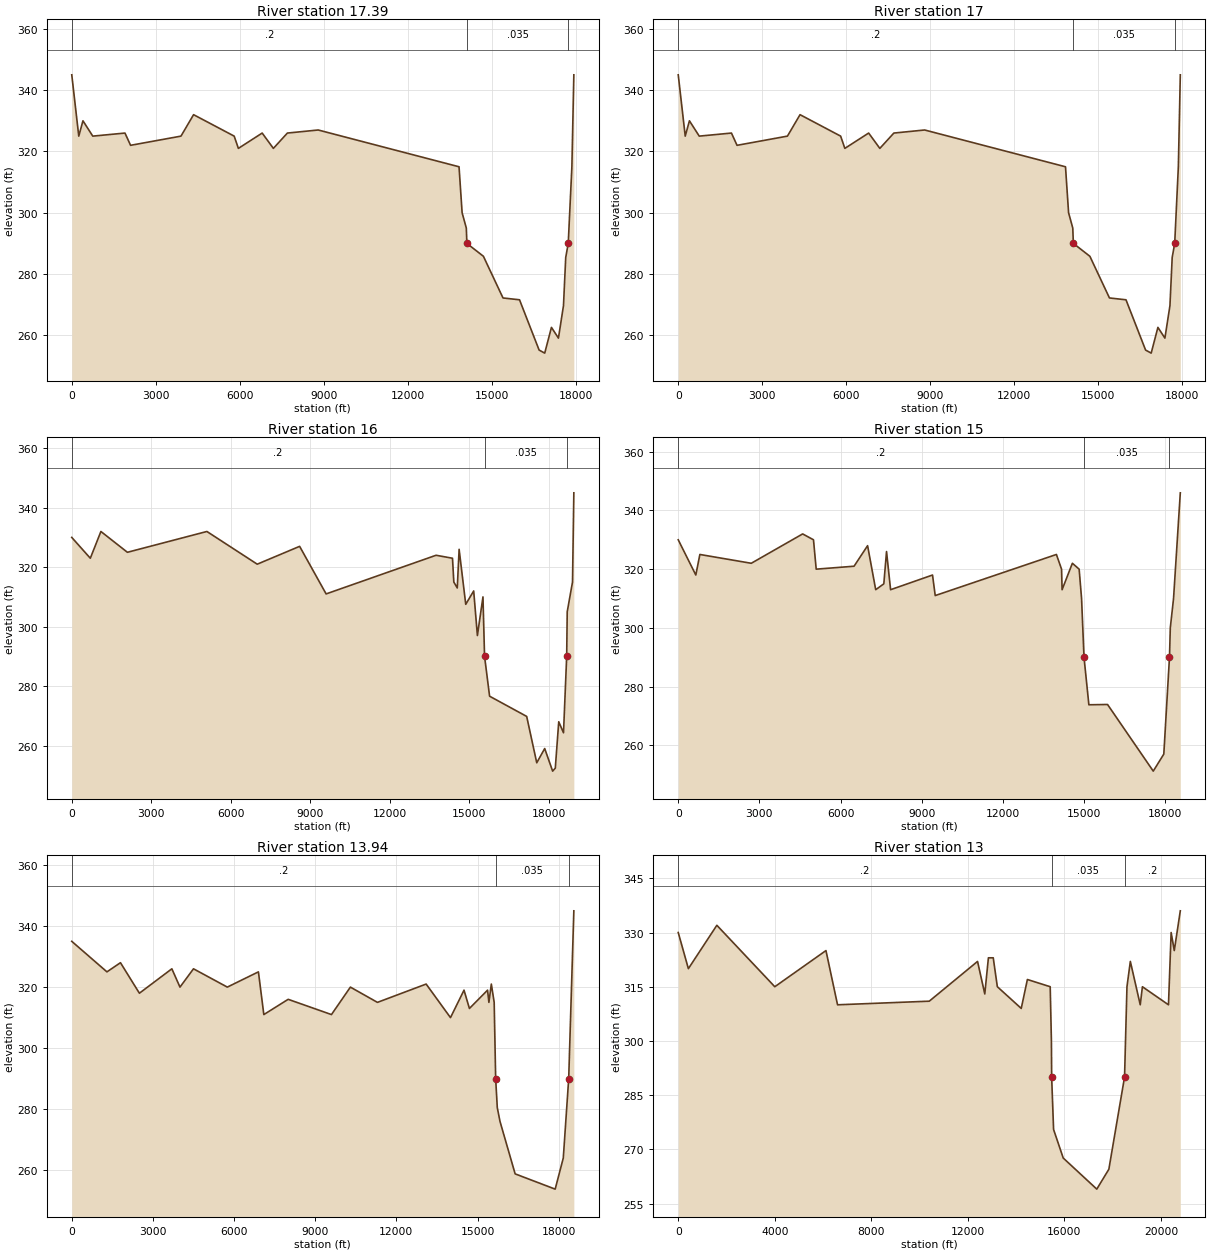
Type RM Length L Ch R = 1 ,17.39   ,2060,2060,2060
#Sta/Elev= 30
       0     345     250     325     400     330     750     325    1900     326
    2100     322    3900     325    4350     332    5800     325    5950     321
    6800     326    7200     321    7700     326    8800     327   13830     315
   13940     300   14090     295   14110     290   14700   285.8   15400   272.2
   15990   271.6   16690   255.2   16890   254.2   17130   262.6   17380   259.1
   17560   269.7   17640   285.4   17730     290   17860     315   17930     345
#Mann= 3 ,0,0
       0      .2       0   14110    .035       0   17730      .2       0
Bank Sta=14110,17730
XS Rating Curve= 0 ,0
Exp/Cntr=0.3,0.1

Type RM Length L Ch R = 1 ,17      ,5300,5280,5300
#Sta/Elev= 30
       0     345     250     325     400     330     750     325    1900     326
    2100     322    3900     325    4350     332    5800     325    5950     321
    6800     326    7200     321    7700     326    8800     327   13830     315
   13940     300   14090     295   14110     290   14700   285.8   15400   272.2
   15990   271.6   16690   255.2   16890   254.2   17130   262.6   17380   259.1
   17560   269.7   17640   285.4   17730     290   17860     315   17930     345
#Mann= 3 ,0,0
       0      .2       0   14110    .035       0   17730      .2       0
Bank Sta=14110,17730
XS Rating Curve= 0 ,0
Exp/Cntr=0.3,0.1

Type RM Length L Ch R = 1 ,16      ,5300,5280,5300
#Sta/Elev= 30
       0     330     700     323    1100     332    2100     325    5100     332
    7000     321    8600     327    9600     311   13750     324   14370     323
   14420     315   14550     313   14620     326   14870   307.5   15170     312
   15310     297   15520     310   15580     290   15770   276.6   17170   269.8
   17550   254.2   17850     259   18150   251.4   18250   252.4   18380     268
   18560   264.3   18680     290   18700     305   18900     315   18950     345
#Mann= 3 ,0,0
       0      .2       0   15580    .035       0   18680      .2       0
Bank Sta=15580,18680
XS Rating Curve= 0 ,0
Exp/Cntr=0.3,0.1

Type RM Length L Ch R = 1 ,15      ,2500,2798.5,2900
#Sta/Elev= 30
       0     330     650     318     800     325    2700     322    4600     332
    5000     330    5100     320    6500     321    7000     328    7300     313
    7600     315    7700     326    7850     313    9400     318    9500     311
   13980     325   14170     320   14190     313   14570     322   14820     320
   14910     310   15000     290   15180   273.8   15870   273.9   17560   251.2
   17950     257   18160     290   18190     300   18310     310   18560     346
#Mann= 3 ,0,0
       0      .2       0   15000    .035       0   18160      .2       0
Bank Sta=15000,18160
XS Rating Curve= 0 ,0
Exp/Cntr=0.3,0.1

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
Type RM Length L Ch R = 1 ,13.94   ,4000,4963,4600
#Sta/Elev= 30
       0     335    1300     325    1800     328    2500     318    3700     326
    4000     320    4500     326    5750     320    6900     325    7100     311
    8000     316    9600     311   10300     320   11300     315   13100     321
   14000     310   14500     319   14700     313   15370     319   15420     315
   15510     321   15615     315   15670     290   15730   280.5   15830     276
   16390   258.8   17870   253.8   18170     264   18370     290   18560     345
#Mann= 3 ,0,0
       0      .2       0   15670    .035       0   18370      .2       0
Bank Sta=15670,18370
XS Rating Curve= 0 ,0
Exp/Cntr=0.3,0.1

Type RM Length L Ch R = 1 ,13      ,5300,5280,5300
#Sta/Elev= 30
       0     330     420     320    1600     332    4000     315    6120     325
    6600     310   10400     311   12400     322   12700     313   12850     323
   13050     323   13220     315   14210     309   14465     317   15410     315
   15460     300   15470     290   15550   275.5   15950   267.6   17340     259
   17840   264.5   18490     290   18590     315   18730     322   19140     310
   19230     315   20310     310   20420     330   20550     325   20800     336
#Mann= 3 ,0,0
       0      .2       0   15470    .035       0   18490      .2       0
Bank Sta=15470,18490
XS Rating Curve= 0 ,0
Exp/Cntr=0.3,0.1

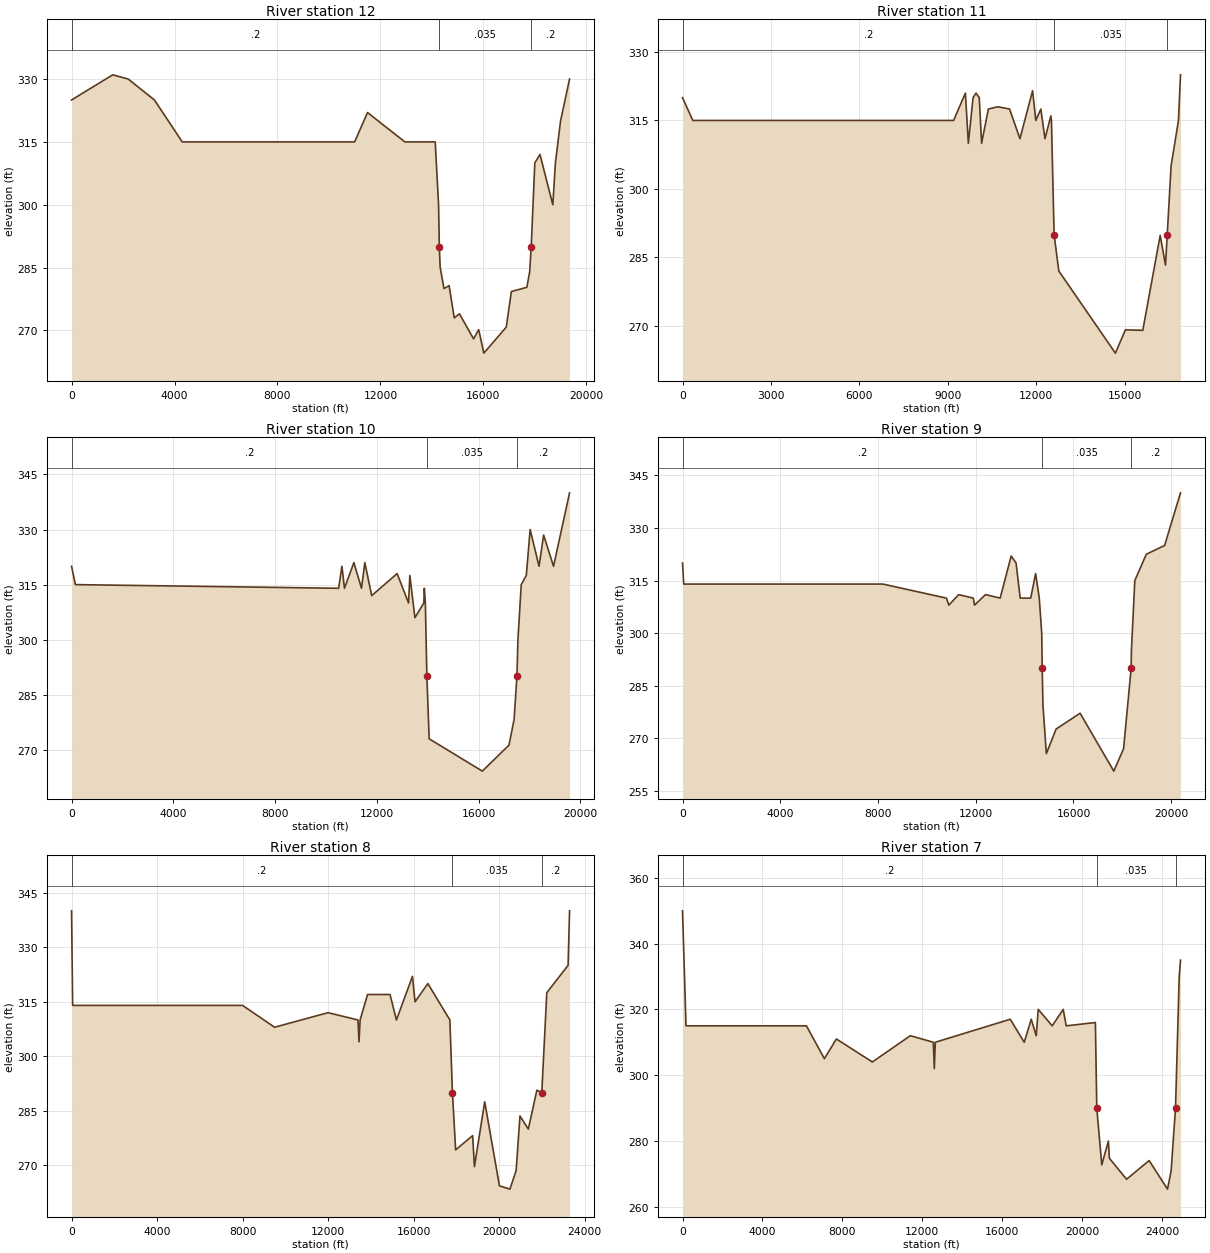
Type RM Length L Ch R = 1 ,12      ,5300,5280,5300
#Sta/Elev= 30
       0     325    1600     331    2200     330    3220     325    4300     315
   11000     315   11500     322   12950     315   14130     315   14260     300
   14290     290   14320   285.2   14470     280   14670   280.7   14870     273
   15070     274   15620     268   15820   270.2   16020   264.6   16890   270.8
   17090   279.3   17690   280.3   17800     284   17860     290   18000     310
   18200     312   18700     300   18800     310   19000     320   19350     330
#Mann= 3 ,0,0
       0      .2       0   14290    .035       0   17860      .2       0
Bank Sta=14290,17860
XS Rating Curve= 0 ,0
Exp/Cntr=0.3,0.1

Type RM Length L Ch R = 1 ,11      ,5100,5280,5300
#Sta/Elev= 30
       0     320     350     315    9200     315    9600     321    9700     310
    9860     320    9960     321   10070     320   10150     310   10380   317.5
   10700     318   11100   317.5   11450     311   11880   321.5   11990     315
   12160   317.5   12300     311   12500     316   12520     315   12610     290
   12770     282   14690     264   15030   269.1   15620     269   16210   289.8
   16390   283.3   16450     290   16580     305   16830     315   16900     325
#Mann= 3 ,0,0
       0      .2       0   12610    .035       0   16450      .2       0
Bank Sta=12610,16450
XS Rating Curve= 0 ,0
Exp/Cntr=0.3,0.1

Type RM Length L Ch R = 1 ,10      ,4500,5280,5300
#Sta/Elev= 30
       0     320     150     315   10500     314   10630     320   10730     314
   11100     321   11400     314   11530     321   11800     312   12800     318
   13250     310   13300   317.5   13500     306   13850     310   13870     314
   13910     310   13970     290   14060     273   16150   264.2   17200   271.3
   17400   278.3   17510     290   17550     300   17680     315   17880   317.5
   18030     330   18380     320   18560   328.5   18950     320   19580     340
#Mann= 3 ,0,0
       0      .2       0   13970    .035       0   17510      .2       0
Bank Sta=13970,17510
XS Rating Curve= 0 ,0
Exp/Cntr=0.3,0.1

Type RM Length L Ch R = 1 ,9       ,4500,5280,5300
#Sta/Elev= 30
       0     320      50     314    8200     314   10800     310   10900     308
   11300     311   11900     310   11950     308   12400     311   13000     310
   13450     322   13650     320   13820     310   14250     310   14450     317
   14600     310   14700     300   14720     290   14750   279.5   14890   265.7
   15290   272.7   16270   277.2   17650   260.7   18050   267.1   18360     290
   18370     295   18510     315   18980   322.5   19730     325   20380     340
#Mann= 3 ,0,0
       0      .2       0   14720    .035       0   18360      .2       0
Bank Sta=14720,18360
XS Rating Curve= 0 ,0
Exp/Cntr=0.3,0.1

Type RM Length L Ch R = 1 ,8       ,4500,5280,5300
#Sta/Elev= 30
       0     340      50     314    8000     314    9500     308   12000     312
   13400     310   13450     304   13500     310   13850     317   14900     317
   15200     310   15950     322   16070     315   16670     320   17700     310
   17820     290   17970   274.3   18765   278.2   18850   269.7   19330   287.5
   20020   264.4   20510   263.5   20800   268.6   20980   283.6   21370     280
   21770   290.7   22000     290   22235   317.5   23230     325   23300     340
#Mann= 3 ,0,0
       0      .2       0   17820    .035       0   22000      .2       0
Bank Sta=17820,22000
XS Rating Curve= 0 ,0
Exp/Cntr=0.3,0.1

Type RM Length L Ch R = 1 ,7       ,2500,2904,2900
#Sta/Elev= 30
       0     350     175     315    6200     315    7100     305    7700     311
    9500     304   11400     312   12550     310   12600     302   12650     310
   16400     317   17100     310   17450     317   17700     312   17800     320
   18500     315   19050     320   19200     315   20660     316   20730     290
   20980   272.7   21310   279.9   21360   274.7   22220   268.3   23350     274
   24270   265.3   24450   270.8   24670     290   24855     330   24920     335
#Mann= 3 ,0,0
       0      .2       0   20730    .035       0   24670      .2       0
Bank Sta=20730,24670
XS Rating Curve= 0 ,0
Exp/Cntr=0.3,0.1

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
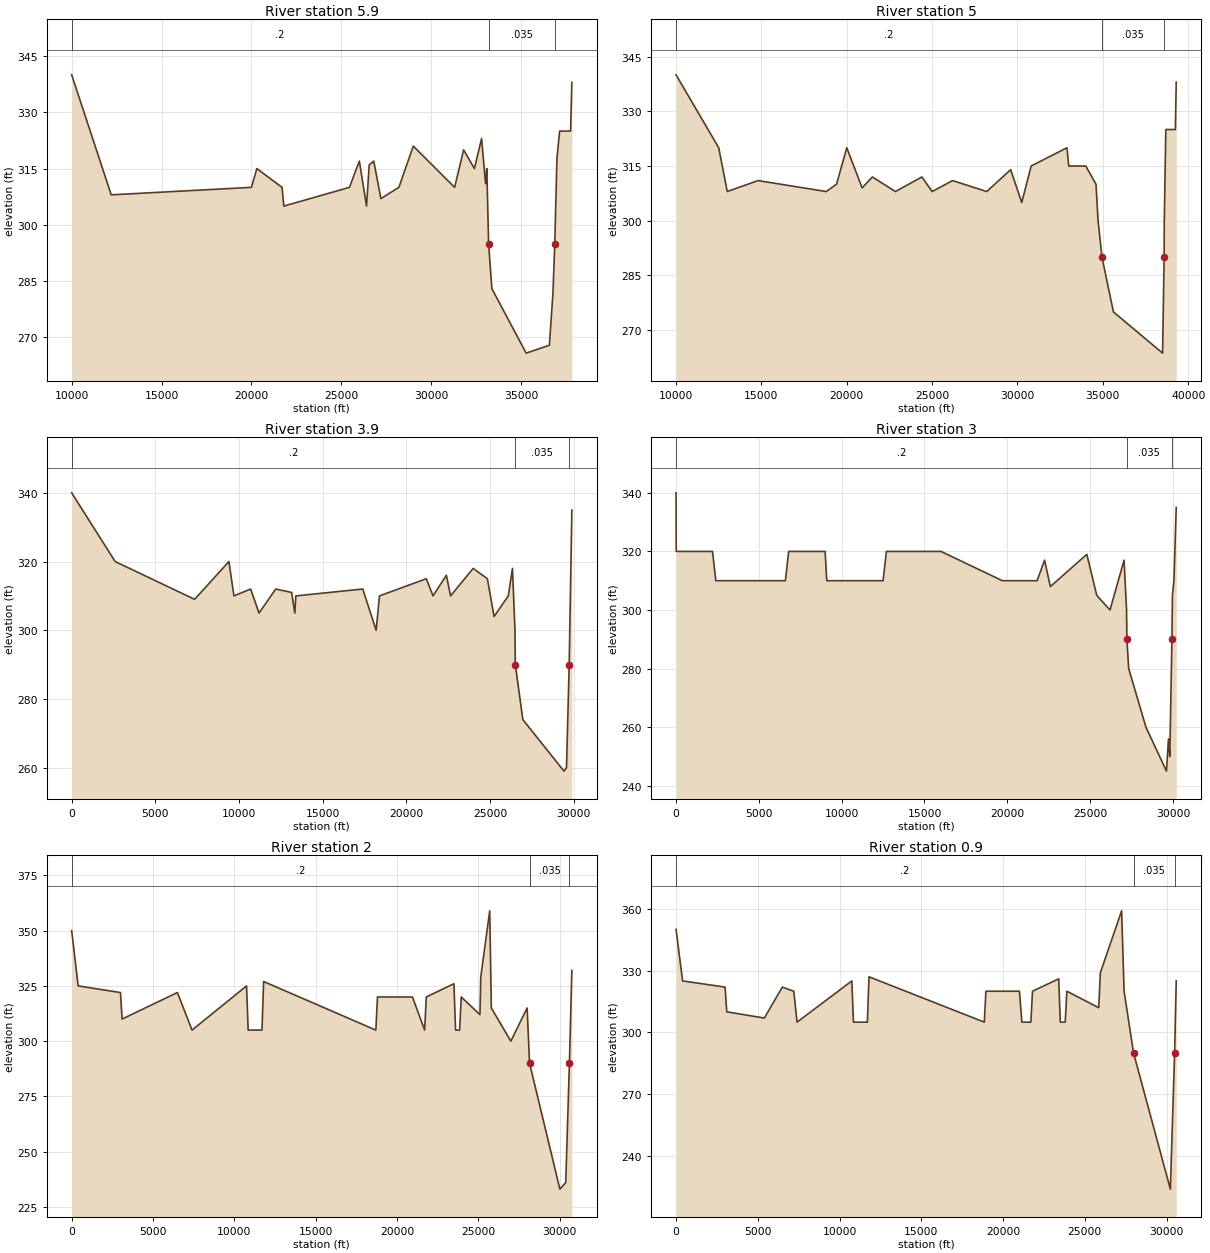
Type RM Length L Ch R = 1 ,5.9     ,4500,4752,4800
#Sta/Elev= 30
   10000     340   12200     308   20000     310   20300     315   21700     310
   21800     305   25450     310   26000     317   26400     305   26550     316
   26800     317   27200     307   28200     310   29000     321   31300     310
   31800     320   32400     315   32800     323   33020     311   33090     315
   33190     295   33370     283   35279   265.8   36570   267.9   36770   281.9
   36870     295   36990   317.7   37140     325   37750     325   37820     338
#Mann= 3 ,0,0
   10000      .2       0   33190    .035       0   36870      .2       0
Bank Sta=33190,36870
XS Rating Curve= 0 ,0
Exp/Cntr=0.3,0.1

Type RM Length L Ch R = 1 ,5       ,2250,2904,2950
#Sta/Elev= 30
   10000     340   12500     320   13000     308   14800     311   18800     308
   19400     310   20000     320   20900     309   21500     312   22850     308
   24400     312   25000     308   26200     311   28200     308   29600     314
   30250     305   30800     315   32900     320   33000     315   34000     315
   34600     310   34720     300   34950     290   35620     275   38500   263.7
   38590     290   38600     300   38690     325   39250     325   39300     338
#Mann= 3 ,0,0
   10000      .2       0   34950    .035       0   38590      .2       0
Bank Sta=34950,38590
XS Rating Curve= 0 ,0
Exp/Cntr=0.3,0.1

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
Type RM Length L Ch R = 1 ,3.9     ,3500,4752,4800
#Sta/Elev= 30
       0     340    2600     320    7350     309    9400     320    9700     310
   10700     312   11200     305   12200     312   13150     311   13340     305
   13400     310   17400     312   18200     300   18400     310   21200     315
   21600     310   22400     316   22650     310   24000     318   24850     315
   25250     304   26100     310   26350     318   26500     300   26520     290
   26970     274   29430     259   29580     260   29740     290   29900     335
#Mann= 3 ,0,0
       0      .2       0   26520    .035       0   29740      .2       0
Bank Sta=26520,29740
XS Rating Curve= 0 ,0
Exp/Cntr=0.3,0.1

Type RM Length L Ch R = 1 ,3       ,4000,5280,5400
#Sta/Elev= 30
       0     340      10     320    2200     320    2400     310    6600     310
    6800     320    9000     320    9100     310   12500     310   12700     320
   16000     320   19700     310   21800     310   22250     317   22600     308
   24800     319   25400     305   26200     300   27050     317   27200     300
   27220     290   27330     280   28370     260   29610     245   29730     256
   29810     250   29940     290   29970     305   30060     310   30200     335
#Mann= 3 ,0,0
       0      .2       0   27220    .035       0   29940      .2       0
Bank Sta=27220,29940
XS Rating Curve= 0 ,0
Exp/Cntr=0.3,0.1

Type RM Length L Ch R = 1 ,2       ,2000,2904,3000
#Sta/Elev= 30
       0     350     400     325    3000     322    3100     310    6500     322
    7400     305   10750     325   10850     305   11700     305   11800     327
   18700     305   18800     320   20950     320   21700     305   21800     320
   23500     326   23600     305   23850     305   23950     320   25100     312
   25150     329   25700     359   25800     315   27000     300   28000     315
   28150     290   30014     233   30374     236   30600     290   30750     332
#Mann= 3 ,0,0
       0      .2       0   28150    .035       0   30600      .2       0
Bank Sta=28150,30600
XS Rating Curve= 0 ,0
Exp/Cntr=0.3,0.1

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
Type RM Length L Ch R = 1 ,0.9     ,5500,4752,4752
#Sta/Elev= 30
       0     350     400     325    3000     322    3100     310    5400     307
    6500     322    7200     320    7400     305   10750     325   10850     305
   11700     305   11800     327   18850     305   18950     320   21000     320
   21150     305   21700     305   21800     320   23400     326   23500     305
   23800     305   23900     320   25850     312   25950     329   27250     359
   27400     320   27980     290   30230     224   30490     290   30590     325
#Mann= 3 ,0,0
       0      .2       0   27980    .035       0   30490      .2       0
Bank Sta=27980,30490
XS Rating Curve= 0 ,0
Exp/Cntr=0.3,0.1

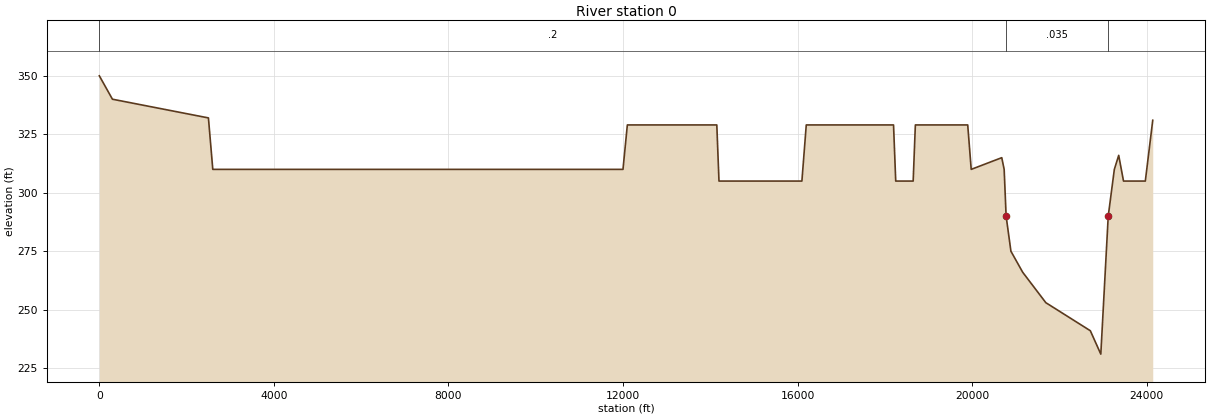
Type RM Length L Ch R = 1 ,0       ,0,,0
#Sta/Elev= 30
       0     350     300     340    2500     332    2600     310   12000     310
   12100     329   14150     329   14200     305   16100     305   16200     329
   18200     329   18250     305   18650     305   18700     329   19900     329
   19980     310   20680     315   20735     310   20780     290   20890     275
   21160     266   21690     253   22710     241   22950     231   23120     290
   23260     310   23360     316   23470     305   23970     305   24140     331
#Mann= 3 ,0,0
       0      .2       0   20780    .035       0   23120      .2       0
Bank Sta=20780,23120
XS Rating Curve= 0 ,0
Exp/Cntr=0.3,0.1

River Reach=Mississippi Riv ,Lower
Reach XY= 23
   567933.755803  226136.1414702  575264.2058038  226520.4192115
  585736.2772335  218491.8311154  586434.4153288  199293.0334943
  583641.8629475  189170.0311123  580500.2415186  177650.7525396
   580151.172471  171018.4406341  579802.1034233  162291.7144427
  578405.8272327  154263.1263466  573169.7915178  145885.4692029
  569876.2112408  139835.6213074    570032.68454  132883.7361528
  570273.5213183  122183.7021464  573169.7915178  113422.0477709
  576660.4819944  105044.3906271  582594.6558046   95270.4572928
  587132.5534241   82005.8334818  582594.6558046   69788.4168139
  581198.3796139   61759.8287178  579453.0343757   50589.6191928
  577707.6891374    42211.962049  575264.2058038   34881.5120483
  574566.0677085   29296.4072858

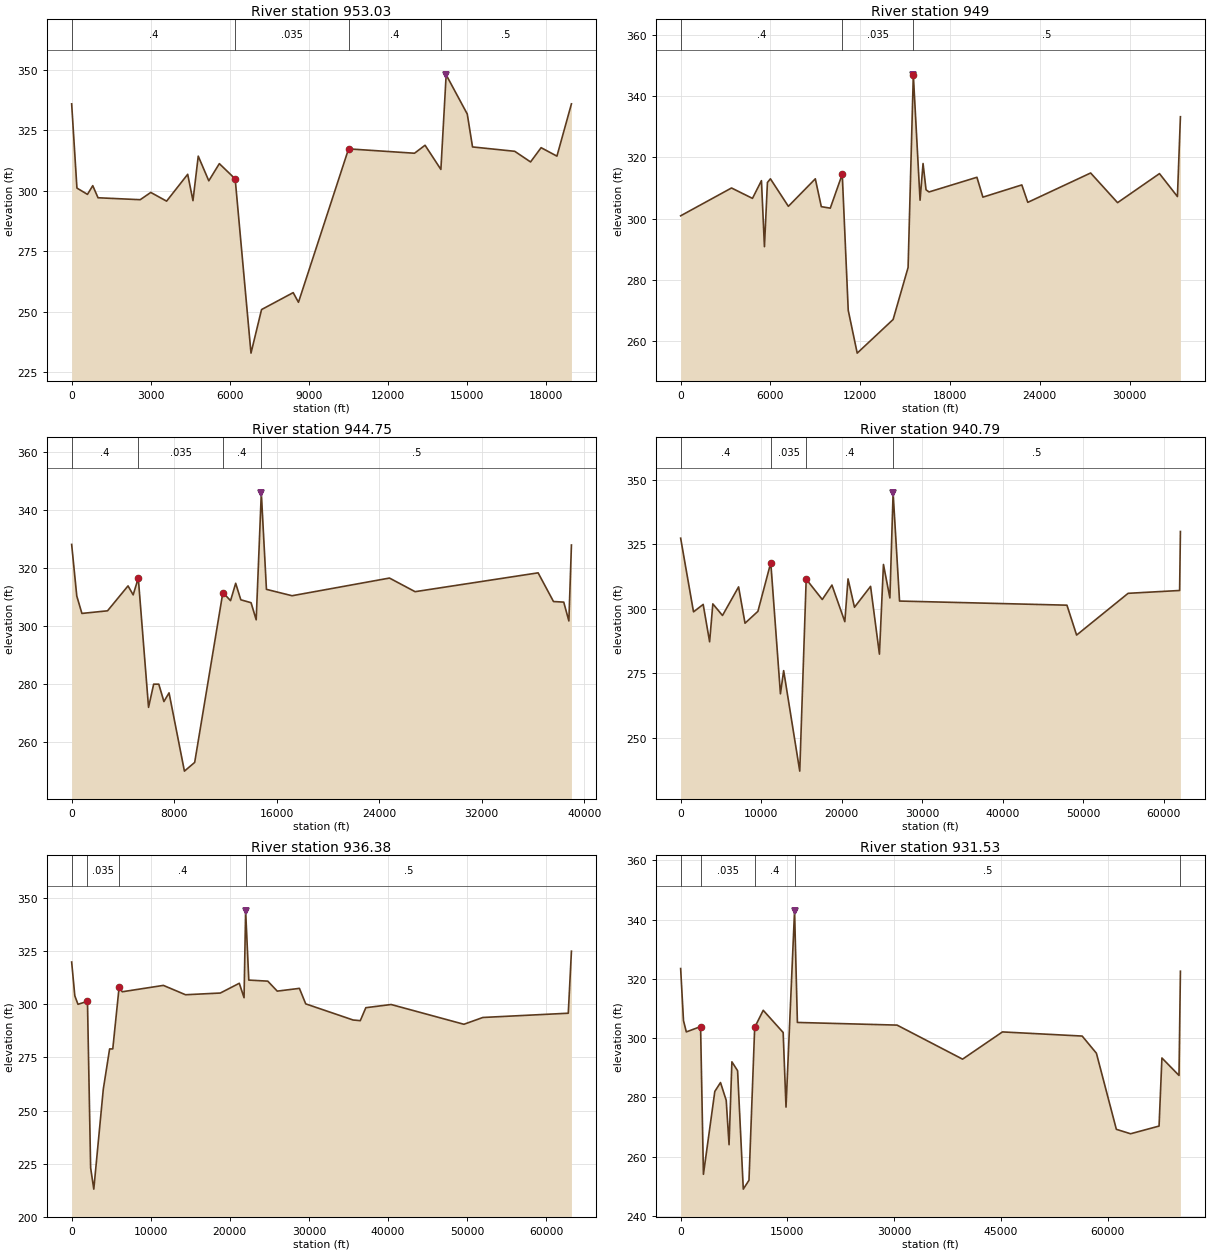
Type RM Length L Ch R = 1 ,953.03  ,4479.2,4255.6,3437.6
#Sta/Elev= 30
       0     336     200   301.2     600   298.6     800   302.2    1000   297.2
    2600   296.4    3000   299.4    3600   295.8    4400   306.9    4600     296
    4800   314.4    5200   304.2    5600   311.3    6200     305    6800     233
    7200     251    8400     258    8600     254   10500   317.4   13000   315.6
   13400   318.9   14000   308.9   14200     348   15000   331.8   15200   318.2
   16800   316.4   17400     312   17800   317.9   18400   314.4   18950     336
#Mann= 4 ,-1,0
       0      .4       0    6200    .035       0   10500      .4       0
   14000      .5       0
Levee=0,,,-1,14200,348,,
Bank Sta=6200,10500
XS Rating Curve= 0 ,0
Exp/Cntr=0.3,0.1

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
Type RM Length L Ch R = 1 ,949     ,4375,4488,4166.6
#Sta/Elev= 30
       0   300.9    3400     310    4800   306.6    5400   312.4    5600   290.8
    5800   311.8    6000     313    7200     304    9000     313    9400   303.9
   10000   303.4   10800   314.5   11200     270   11800     256   14200     267
   15200     284   15550     347   16000     306   16200     318   16400   309.4
   16600   308.7   19800   313.5   20200     307   22800     311   23200   305.3
   27400   314.9   29200   305.2   32000   314.7   33200   307.2   33400   333.3
#Mann= 3 ,0,0
       0      .4       0   10800    .035       0   15550      .5       0
Levee=0,,,-1,15550,347,,
Bank Sta=10800,15550
XS Rating Curve= 0 ,0
Exp/Cntr=0.3,0.1

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
Type RM Length L Ch R = 1 ,944.75  ,3854.2,4181.8,4583.4
#Sta/Elev= 30
       0   328.2     400   310.4     800   304.4    2800   305.3    4400   313.9
    4800   310.8    5200   316.6    6000     272    6400     280    6800     280
    7200     274    7600     277    8800     250    9600     253   11800   311.6
   12400   308.8   12800   314.8   13200   309.1   14000   308.1   14400   302.2
   14800     346   15200   312.7   17200   310.5   24800   316.6   26800   311.9
   36400   318.4   37600   308.5   38400   308.3   38800   301.8   39000     328
#Mann= 4 ,-1,0
       0      .4       0    5200    .035       0   11800      .4       0
   14800      .5       0
Levee=0,,,-1,14800,346,,
Bank Sta=5200,11800
XS Rating Curve= 0 ,0
Exp/Cntr=0.3,0.1

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
Type RM Length L Ch R = 1 ,940.79  ,4166.6,4657,3958.4
#Sta/Elev= 30
       0   327.4    1600   298.8    2800   301.7    3600   287.2    4000   301.9
    5200   297.4    7200   308.5    8000   294.4    9600     299   11200   317.9
   12400     267   12800     276   14800     237   15600   311.5   17600   303.6
   18800   309.2   20400     295   20800   311.6   21600   300.6   23600   308.7
   24700   282.4   25200   317.2   26000   304.2   26400     345   27200     303
   48000   301.4   49200   289.8   55600     306   62000   307.1   62100     330
#Mann= 4 ,-1,0
       0      .4       0   11200    .035       0   15600      .4       0
   26400      .5       0
Levee=0,,,-1,26400,345,,
Bank Sta=11200,15600
XS Rating Curve= 0 ,0
Exp/Cntr=0.3,0.1

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
Type RM Length L Ch R = 1 ,936.38  ,3689.17,4268,4774.17
#Sta/Elev= 30
       0   319.9     400     304     800     300    2000   301.4    2400     223
    2800     213    4000     260    4800     279    5200     279    6000     308
    6400   305.9   11600   308.9   14400   304.5   18800   305.3   21200   309.9
   21800   303.1   22000     344   22400   311.4   24800   310.9   26000   306.2
   28800   307.5   29600   300.2   35600   292.6   36500   292.3   37200   298.4
   40400   299.9   49600   290.6   52000   293.8   62800   295.8   63200     325
#Mann= 4 ,-1,0
       0      .4       0    2000    .035       0    6000      .4       0
   22000      .5       0
Levee=0,,,-1,22000,344,,
Bank Sta=2000,6000
XS Rating Curve= 0 ,0
Exp/Cntr=0.3,0.1

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
Type RM Length L Ch R = 1 ,931.53  ,4270.8,4255.6,3468.8
#Sta/Elev= 30
       0   323.5     400   305.9     800   302.1    2800   303.9    3200     254
    4800     282    5600     285    6400     279    6800     264    7200     292
    8000     289    8800     249    9600     252   10400   303.6   11600   309.4
   14400   301.9   14800   276.7   16000     343   16400   305.3   30400   304.4
   39600   292.9   45200   302.1   56400   300.7   58400   294.9   61200   269.2
   63200   267.7   67200   270.3   67600   293.3   70000   287.4   70200   322.6
#Mann= 5 ,-1,0
       0      .4       0    2800    .035       0   10400      .4       0
   16000      .5       0   70200      .5       0
Levee=0,,,-1,16000,343,,
Bank Sta=2800,10400
XS Rating Curve= 0 ,0
Exp/Cntr=0.3,0.1

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
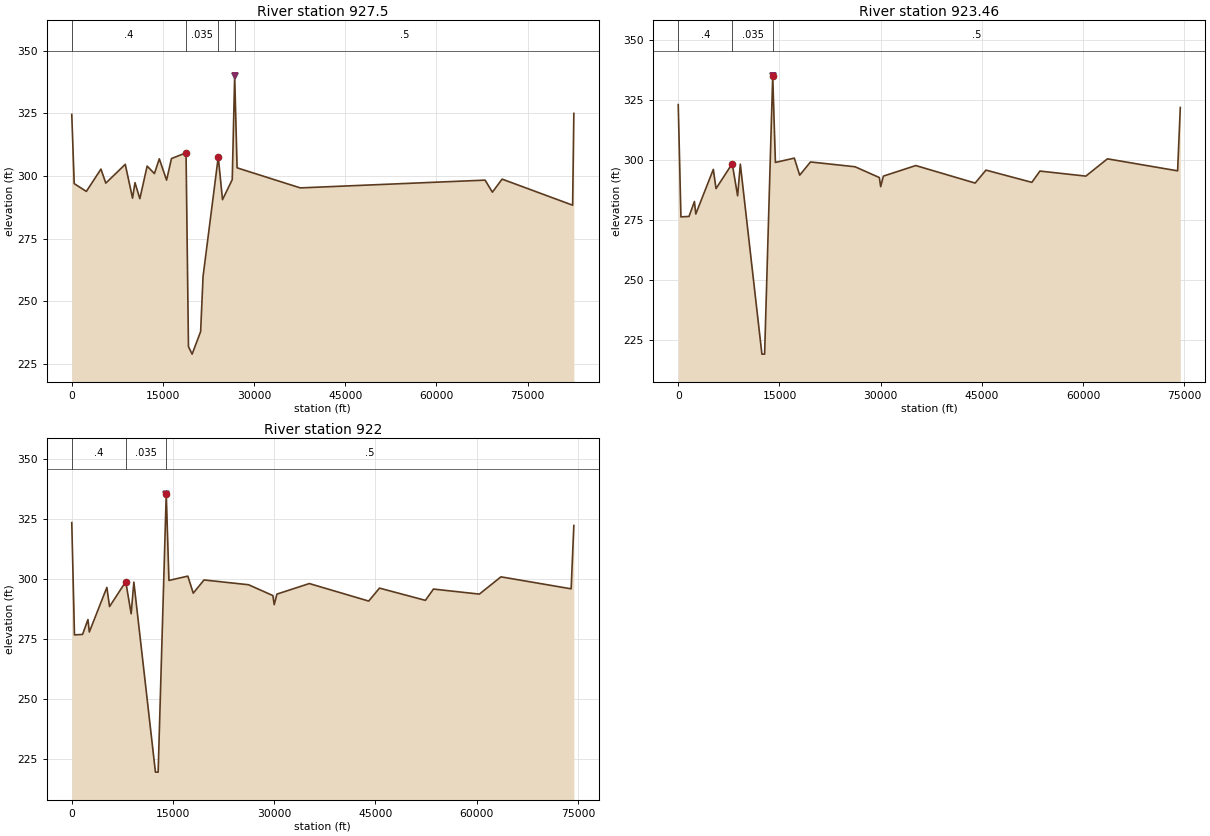
Type RM Length L Ch R = 1 ,927.5   ,4062.6,4266.2,4687.4
#Sta/Elev= 30
       0   324.6     400     297    2400   293.9    4800   302.8    5600   297.2
    8800   304.7   10000   291.2   10400   297.4   11200     291   12400     304
   13600     301   14400   306.9   15600   298.4   16400     307   18800   309.3
   19200     232   19800     229   21200     238   21600     260   24100   307.6
   24800   290.6   26400   298.6   26800     340   27200   303.3   37600   295.3
   68000   298.4   69200   293.6   70800   298.8   82400   288.4   82600     325
#Mann= 4 ,-1,0
       0      .4       0   18800    .035       0   24100      .4       0
   26800      .5       0
Levee=0,,,-1,26800,340,,
Bank Sta=18800,24100
XS Rating Curve= 0 ,0
Exp/Cntr=0.3,0.1

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
Type RM Length L Ch R = 1 ,923.46  ,3759.5,3854.5,2718.5
#Sta/Elev= 30
       0     323     400   276.2    1600   276.4    2400   282.6    2600   277.4
    5200     296    5600     288    8000   298.4    8800     285    9200   298.2
   12400     219   12800     219   14000     335   14400   298.9   17200   300.7
   18000   293.6   19600   299.1   26200   297.1   29800   292.6   30000   288.8
   30400   293.2   35200   297.6   44000   290.3   45600   295.7   52400   290.6
   53600   295.3   60400   293.2   63600   300.4   74000   295.4   74400   321.8
#Mann= 3 ,0,0
       0      .4       0    8000    .035       0   14000      .5       0
Levee=0,,,-1,14000,335,,
Bank Sta=8000,14000
XS Rating Curve= 0 ,0
Exp/Cntr=0.3,0.1

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
Type RM Length L Ch R = 1 ,922     ,14166,13675,9667
#Sta/Elev= 30
       0   323.5     400   276.7    1600   276.9    2400   283.1    2600   277.9
    5200   296.5    5600   288.5    8000   298.9    8800   285.5    9200   298.7
   12400   219.5   12800   219.5   14000   335.5   14400   299.4   17200   301.2
   18000   294.1   19600   299.6   26200   297.6   29800   293.1   30000   289.3
   30400   293.7   35200   298.1   44000   290.8   45600   296.2   52400   291.1
   53600   295.8   60400   293.7   63600   300.9   74000   295.9   74400   322.3
#Mann= 3 ,0,0
       0      .4       0    8000    .035       0   14000      .5       0
Levee=0,,,-1,14000,335,,
Bank Sta=8000,14000
XS Rating Curve= 0 ,0
Exp/Cntr=0.3,0.1
LCMann Table=0

Chan Stop Cuts=-1
Use User Specified Reach Order=0
User Specified Reach Order=Mississippi Riv ,Upper
User Specified Reach Order=Ohio River      ,Main Stem
User Specified Reach Order=Mississippi Riv ,Lower
Composite Channel Slope=5